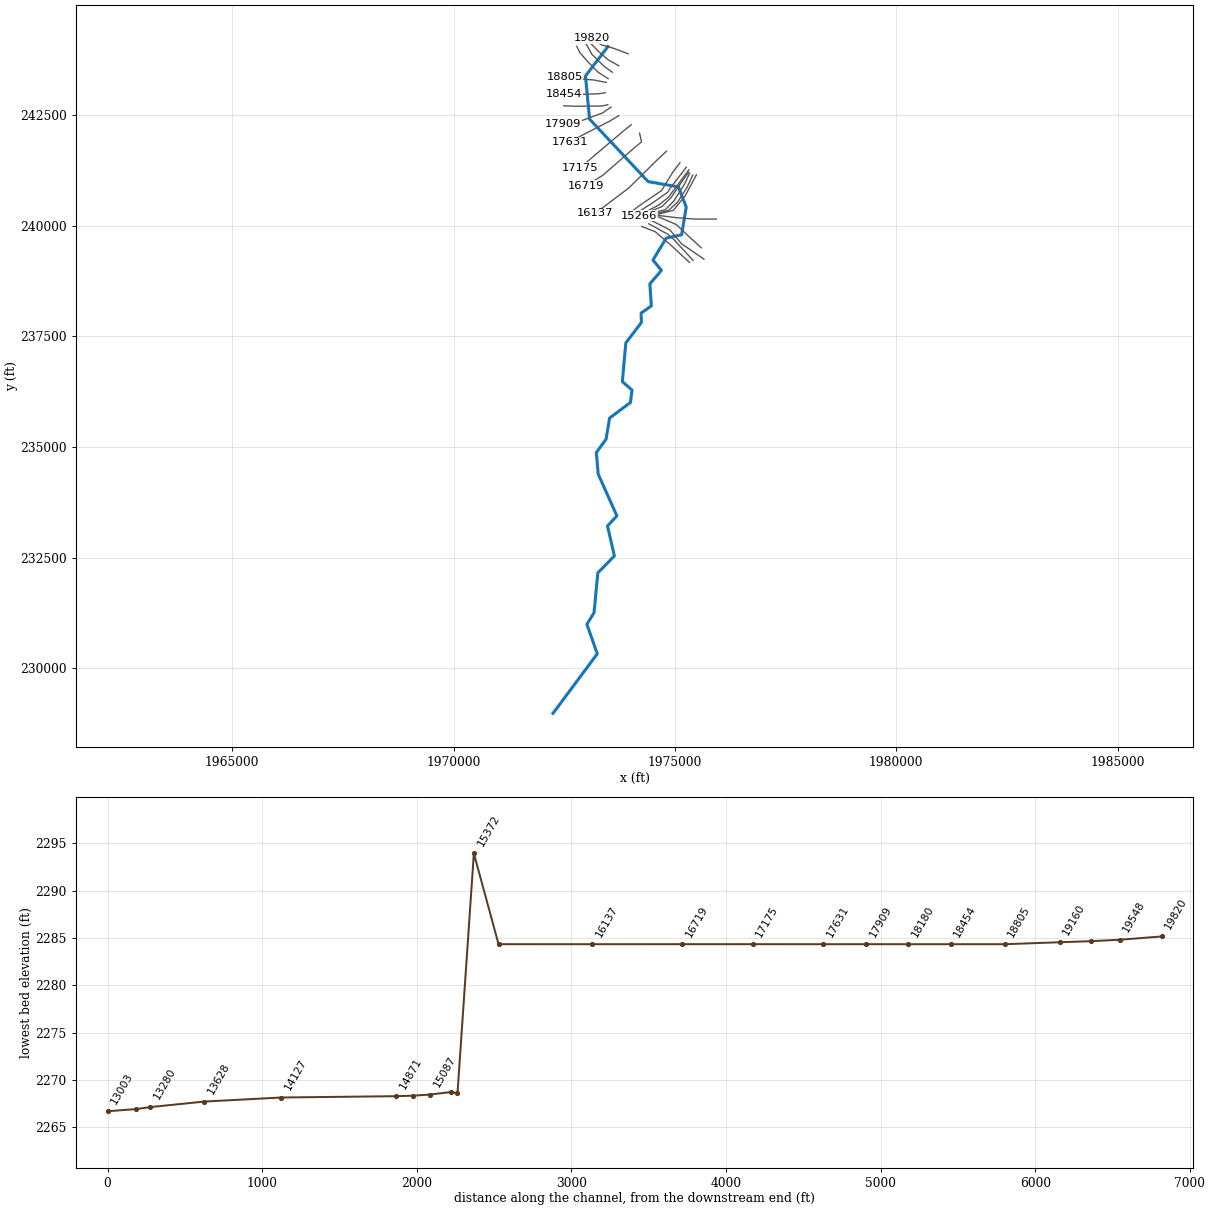
--- JUMPNGBR.prj (project) ---

Proj Title=JUMPNGBR
Current Plan=p01
Default Exp/Contr=0,0
English Units
Geom File=g01
Flow File=f01
Plan File=p01
Background Map Layer=Final_Streamlines
Background Map Layer=Shifted_Points
Background Map Layer=QC
BEGIN DESCRIPTION:
Stream Name: Jumping Branch
Flood Zone: Approximate
Summers County, West Virginia
HEC-RAS Version: 5.0.7
Hydrology Method:
Regression.
Model Notes:
END DESCRIPTION:
DSS File=dss
DSS Export Rating Curves= 0
DSS Export Rating Curve Sorted= 0
DSS Export Volume Flow Curves= 0
DXF OffsetX= 0
DXF OffsetY= 0
DXF ScaleX= 0
DXF ScaleY= 0

--- JUMPNGBR.p01 (plan) ---

Plan Title=Floodplain
Program Version=5.07
Short Identifier=Floodplain
Geom File=g01
Flow File=f01
Subcritical Flow
K Sum by GR= 0
Std Step Tol= 0.01
Critical Tol= 0.01
Num of Std Step Trials= 20
Max Error Tol= 0.3
Flow Tol Ratio= 0.001
Split Flow NTrial= 30
Split Flow Tol= 0.02
Split Flow Ratio= 0.02
Log Output Level= 0
Friction Slope Method= 1
Unsteady Friction Slope Method= 2
Unsteady Bridges Friction Slope Method= 1
Parabolic Critical Depth
Global Vel Dist= 0 , 0 , 0
Global Log Level= 0
CheckData=True
Encroach Param=-1 ,0,0, 0
Computation Interval=0.1SEC
Output Interval=1MIN
Instantaneous Interval=Max Profile
Mapping Interval=1HOUR
Computation Time Step Use Courant=        0
Computation Time Step Use Time Series=    0
Computation Time Step Count To Double=0
Computation Time Step Max Doubling=0
Computation Time Step Max Halving=0
Computation Time Step Residence Courant=0
Run HTab= 0
Run UNet= 0
Run Sediment= 0
Run PostProcess= 0
Run WQNet= 0
Run RASMapper= 0
UNET Theta= 0
UNET Theta Warmup= 0
UNET ZTol= 0
UNET ZSATol= 0
UNET MxIter= 0
UNET Max Iter WO Improvement= 0
UNET MaxInSteps= 0
UNET DtIC= 0
UNET DtMin= 0
UNET MaxCRTS= 0
UNET WFStab= 0
UNET SFStab= 0
UNET WFX= 1
UNET SFX= 1
UNET 1D Methodology=Finite Difference
UNET DSS MLevel= 1
UNET Pardiso=0
UNET DZMax Abort= 0
UNET Use Existing IB Tables= 0
UNET Froude Reduction=False
UNET Froude Limit= 0
UNET Froude Power= 0
UNET D1 Cores= 0
UNET D2 Coriolis=0
UNET D2 Cores= 0
UNET D2 Theta= 1
UNET D2 Theta Warmup= 1
UNET D2 Z Tol= 0.01
UNET D2 Volume Tol= 0.01
UNET D2 Max Iterations= 20
UNET D2 Equation= 0
UNET D2 RampUpFraction=0.1
UNET D2 TimeSlices= 1
UNET D2 BCVolumeCheck=0
UNET D1D2 MaxIter= 0
UNET D1D2 ZTol=0.01
UNET D1D2 QTol=0.1
UNET D1D2 MinQTol=1
DSS File=dss
Write IC File= 0
Write IC File at Fixed DateTime=0
Write IC File at Sim End=0
Echo Input=False
Echo Parameters=False
Echo Output=False
Write Detailed= 0
HDF Write Warmup=0
HDF Write Time Slices=0
HDF Flush=0
HDF Face Node Velocities=0
HDF Compression= 1
HDF Chunk Size= 1
HDF Spatial Parts= 1
HDF Use Max Rows=0
HDF Fixed Rows= 1
Calibration Method= 0
Calibration Iterations= 20
Calibration Max Change=0.05
Calibration Tolerance=0.2
Calibration Maximum=1.5
Calibration Minimum=0.5
Calibration Optimization Method= 1
WQ AD Non Conservative
WQ ULTIMATE=-1
WQ Max Comp Step=1HOUR
WQ Output Interval=15MIN
WQ Output Selected Increments= 0
WQ Output face flow=0
WQ Output face velocity=0
WQ Output face area=0
WQ Output face dispersion=0
WQ Output cell volume=0
WQ Output cell surface area=0
WQ Output cell continuity=0
WQ Output cumulative cell continuity=0
WQ Output face conc=0
WQ Output face dconc_dx=0
WQ Output face courant=0
WQ Output face peclet=0
WQ Output face adv mass=0
WQ Output face disp mass=0
WQ Output cell mass=0
WQ Output cell source sink temp=0
WQ Output nsm pathways=0
WQ Output nsm derived pathways=0
WQ Output MaxMinRange=-1
WQ Daily Max Min Mean=-1
WQ Daily Range=0
WQ Daily Time=0
WQ Create Restart=0
WQ Fixed Restart=0
WQ System Summary=0
WQ Write To DSS=0
WQ Use Fixed Temperature=0
Sorting and Armoring Iterations= 10
XS Update Threshold= 0.02
Bed Roughness Predictor= 0
Hydraulics Update Threshold= 0.02
Energy Slope Method= 1
Volume Change Method= 1
Sediment Retention Method= 0
XS Weighting Method= 0
Number of US Weighted Cross Sections= 1
Number of DS Weighted Cross Sections= 1
Upstream XS Weight=0
Main XS Weight=1
Downstream XS Weight=0
Number of DS XS's Weighted with US Boundary= 1
Upstream Boundary Weight= 1
Weight of XSs Associated with US Boundary= 0
Number of US XS's Weighted with DS Boundary= 1
Downstream Boundary Weight= 0.5
Weight of XSs Associated with DS Boundary= 0.5
Percentile Method= 0
Sediment Output Level= 3
Mass or Volume Output= 0
Output Increment Type= 1
Profile and TS Output Increment= 1
XS Output Flag= 0
XS Output Increment= 10
Write Gradation File= 0
Read Gradation Hotstart= 0
Write HDF5 File= 1
Write Binary Output= 1
Write DSS Sediment File= 0
SV Curve= 0
Specific Gage Flag= 0

--- JUMPNGBR.f01 (steady flow) ---

Flow Title=Flows
Program Version=5.07
Number of Profiles= 6
Profile Names=01pct,10pct,04pct,02pct,0_2pct,01plus
River Rch & RM=JUMPNGBR,Main            ,19820
     438     229     306     370     615     648
River Rch & RM=JUMPNGBR,Main            ,19548
     585     310     412     496     817     866
River Rch & RM=JUMPNGBR,Main            ,18805
     698     372     492     592     971    1032
River Rch & RM=JUMPNGBR,Main            ,14127
     891     479     632     757    1234    1318
River Rch & RM=JUMPNGBR,Main            ,11252
    1002     541     712     852    1385    1481
River Rch & RM=JUMPNGBR,Main            ,8636
    1162     631     828     989    1601    1718
River Rch & RM=JUMPNGBR,Main            ,3677
    1298     708     927    1107    1785    1920
River Rch & RM=JUMPNGBR,Main            ,18
    2050    1138    1478    1755    2796    3032
Boundary for River Rch & Prof#=JUMPNGBR,Main            , 1
Up Type= 0
Dn Type= 1
Dn Known WS=1744.5
Boundary for River Rch & Prof#=JUMPNGBR,Main            , 2
Up Type= 0
Dn Type= 1
Dn Known WS=1743
Boundary for River Rch & Prof#=JUMPNGBR,Main            , 3
Up Type= 0
Dn Type= 1
Dn Known WS=1743.6
Boundary for River Rch & Prof#=JUMPNGBR,Main            , 4
Up Type= 0
Dn Type= 1
Dn Known WS=1744
Boundary for River Rch & Prof#=JUMPNGBR,Main            , 5
Up Type= 0
Dn Type= 1
Dn Known WS=1745.5
Boundary for River Rch & Prof#=JUMPNGBR,Main            , 6
Up Type= 0
Dn Type= 1
Dn Known WS=1745.7
DSS Import GetInterval= 0
DSS Import GetPeak= 0
DSS Import FillOption= 0

--- JUMPNGBR.g01 (geometry) ---

Geom Title=Geometry
Program Version=5.07

River Reach=JUMPNGBR        ,Main
Reach XY= 30
1973486.78599999244048.6260000141972979.56386242243384.131661083
1973071.67200002242409.6940000211974394.93499999240996.825999998
1975078.84598363240877.0582939611975254.53288577240422.701498231
1975150.99600001239795.710999984     1974802.832239720.341000037
1974503.42300002239223.968000035     1974695.225238991.138000002
1974433.75200001238685.238999994     1974467.456238189.223000026
1974234.80800002238023.7769999671974243.50900001237814.514999997
     1973890.355237350.648999996     1973812.788236477.967000015
     1974030.053236287.2029999781973995.39900002236006.936000027
1973522.48200002 235651.033000021973444.70400001 235175.33900005
      1973225.26234875.3389999911973266.92599999234387.144000002
     1973688.454 233444.08900003     1973477.394233214.249000022
1973632.34199999232537.4259999861973258.59300002232154.505999998
     1973173.401231256.7030000281973011.37100001230992.005999981
1973246.74799999230326.8770000291972246.19517063228980.000779947

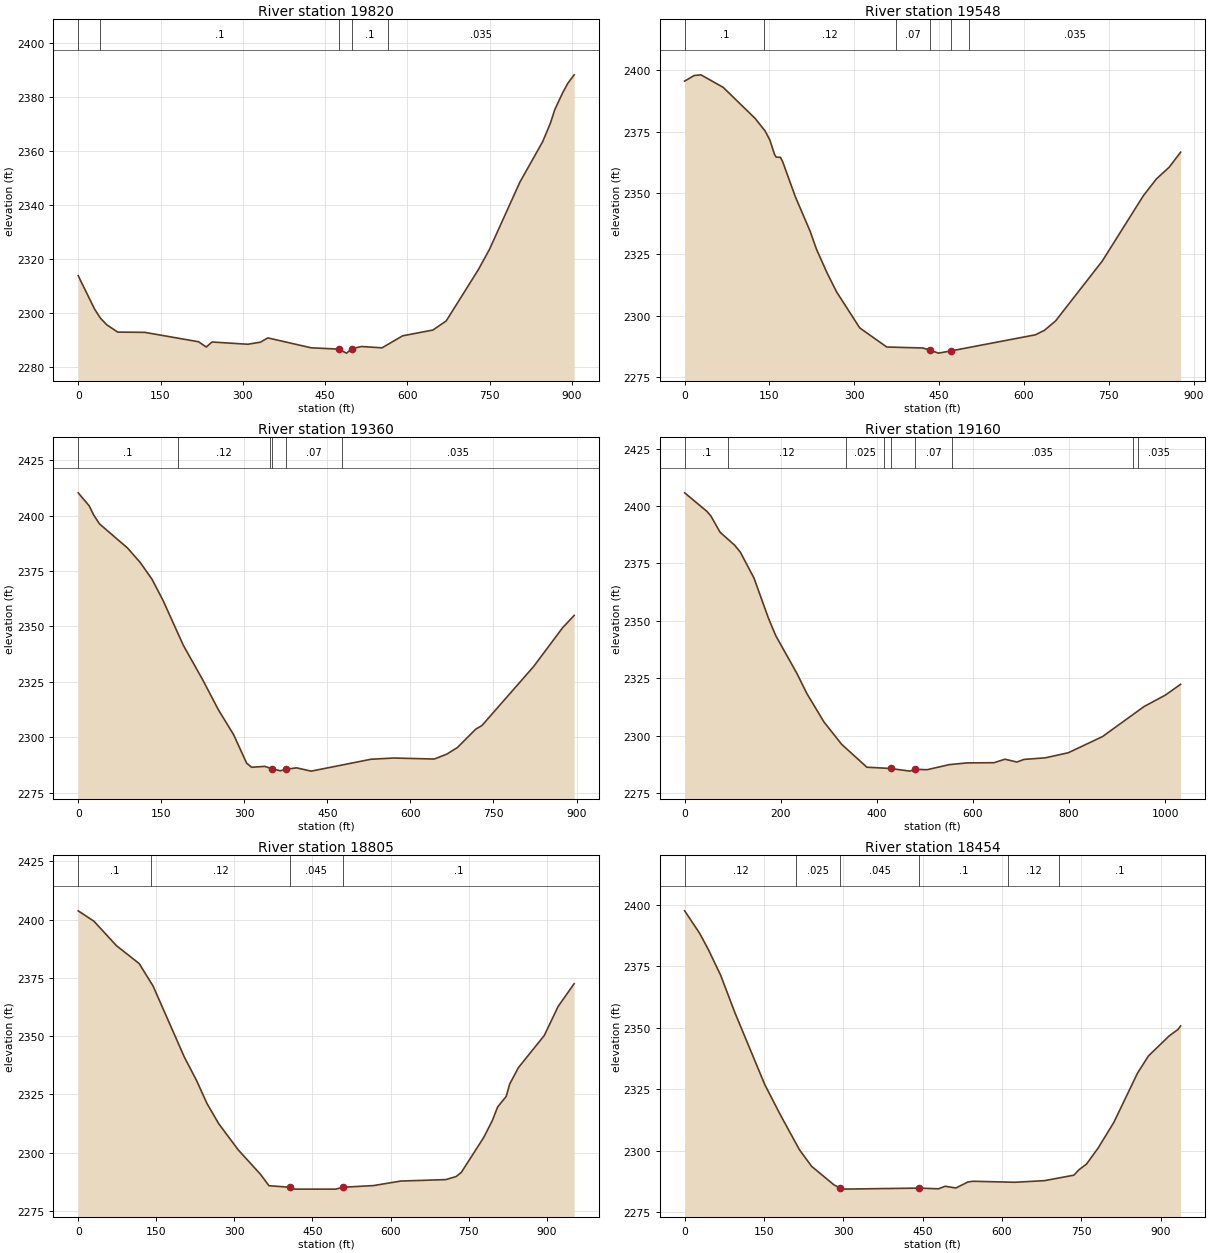
Type RM Length L Ch R = 1 ,19820   ,274.2,272.2,250.3
XS GIS Cut Line= 4
1973945.57032701243884.4105282631973605.24084904244013.153587363
1973338.79869195244087.0409082381973120.49524391244234.815549987
#Sta/Elev= 30
       0 2313.83    29.9 2301.45    40.4 2298.15    52.1 2295.66      72 2292.95
   121.1 2292.86   219.3 2289.38   233.4 2287.43   243.9 2289.28   309.2 2288.45
   332.1 2289.21   345.6  2290.8   424.5 2287.14   474.5 2286.64   489.1 2285.16
   499.4 2286.86   516.4 2287.61   553.8 2287.12   591.3 2291.57   646.6 2293.72
   670.8 2297.09   729.3 2316.06   749.7 2323.61   805.2 2348.55   846.4 2363.41
   860.6 2370.27   868.5 2375.27   883.2 2381.66   892.6 2385.16     904 2388.26
#Mann= 5 ,-1 , 0
       0     .12       0      40      .1       0   474.5    .045       0
   499.4      .1       0  563.87    .035       0
Bank Sta=474.5,499.4
XS Rating Curve= 0 ,0
Exp/Cntr(USF)=0,0
Exp/Cntr=0.3,0.1

Type RM Length L Ch R = 1 ,19548   ,189.8,188.3,193
XS GIS Cut Line= 4
1973731.02620394243615.9781403031973491.92207915243748.660197991
1973256.96426866243954.593808361 1973055.1769726244164.673733033
#Sta/Elev= 30
       0 2395.64    16.7  2397.9    28.7 2398.19      68 2393.11   124.3 2380.51
   142.2 2375.35   150.6 2371.66     159 2365.74   161.9 2364.66   169.4 2364.57
   173.1 2362.94   195.6 2348.61   221.9 2334.46   233.1 2327.16   251.9 2317.48
   268.9 2309.68   309.7 2295.07   357.5  2287.3   421.3  2286.9   434.4 2285.97
   449.1 2284.81   470.9 2285.71   620.3 2292.27   636.3  2294.1     656 2297.92
   738.6 2322.31   811.4 2348.98   834.6 2355.83   856.9 2360.53   877.2 2366.68
#Mann= 6 ,-1 , 0
       0      .1       0     140     .12       0  373.45     .07       0
   434.4    .045       0   470.9     .12       0  503.45    .035       0
Bank Sta=434.4,470.9
XS Rating Curve= 0 ,0
Exp/Cntr(USF)=0,0
Exp/Cntr=0.3,0.1

Type RM Length L Ch R = 1 ,19360   ,193.3,199.8,201.5
XS GIS Cut Line= 4
1973585.90520335243468.0929301721973395.17474542 243606.30340693
1973122.90010621243875.8138366081972990.21804852244119.064275703
#Sta/Elev= 30
       0 2410.37    19.9 2404.48    27.6 2400.52    38.3 2396.37    88.7 2385.53
   112.2 2378.84   133.4 2371.29   153.6 2361.57     190 2341.43     225 2325.84
   252.9  2312.5   280.8 2301.07   304.2 2288.26   313.2  2286.4   336.9 2286.81
   349.9 2285.74   364.8 2284.81   375.9 2285.53   394.4 2286.14   420.8 2284.66
     529 2290.03     570 2290.58   643.2 2290.12   665.7 2292.35   684.8 2295.31
     718 2303.63   729.2 2305.26   822.6 2331.94   874.9 2349.45   895.7 2354.98
#Mann= 6 ,-1 , 0
       0      .1       0     180     .12       0  345.54     .07       0
   349.9    .045       0   375.9     .07       0  475.54    .035       0
Bank Sta=349.9,375.9
XS Rating Curve= 0 ,0
Exp/Cntr(USF)=0,0
Exp/Cntr=0.3,0.1

Type RM Length L Ch R = 1 ,19160   ,292.3,355,382.3
XS GIS Cut Line= 5
1973490.53997438243322.971929576 1973259.7284782243473.621349243
1973023.38856294243716.8717883371972859.69553676243902.853445069
1972781.47286501244053.499896097
#Sta/Elev= 30
       02405.788   46.372397.698  54.5272395.709  73.7952388.591 104.1152382.959
 115.9682379.916 144.316 2368.63 174.5782351.061 189.4552343.612 234.4262326.791
 254.0152318.464 290.1082305.908 326.7032296.246  379.222286.252   428.62285.701
 468.5082284.547   480.42285.335 504.5072285.164 550.9762287.377 588.0332288.137
 643.7722288.212 666.662 2289.74 691.4912288.502 706.3882289.652 750.3722290.335
 798.4492292.546 869.5732299.583 956.2012312.6871000.5622317.6671032.2852322.383
#Mann= 9 ,-1 , 0
       0      .1       0      90     .12       0  335.63    .025       0
  415.63     .07       0   428.6    .045       0   480.4     .07       0
  555.63    .035       0  932.54      .1       0  942.54    .035       0
Bank Sta=428.6,480.4
XS Rating Curve= 0 ,0
Exp/Cntr(USF)=0,0
Exp/Cntr=0.3,0.1

Type RM Length L Ch R = 1 ,18805   ,324.3,350.7,348
XS GIS Cut Line= 4
1973451.84104089243238.6635387541973164.36324923243293.947729457
1972800.86969536243322.971929576 1972509.2455894243369.963491674
#Sta/Elev= 30
       0 2403.77    30.2 2399.32    73.6 2388.79   117.1 2381.14   143.8 2371.52
   203.9 2341.01   227.3    2331   247.4 2321.09   269.9 2312.45   307.3 2301.22
   350.1 2290.73   366.5  2285.8   406.6 2285.15   415.9 2284.34     495 2284.34
   508.1 2285.14   567.3 2285.86   619.9 2287.81     706 2288.42   725.9 2289.72
   735.9 2291.48   779.1 2306.53   795.7  2313.8   805.7 2319.57   822.3 2324.14
   828.9 2329.41   845.7 2336.48   895.4 2350.27     922 2362.73   952.8  2372.5
#Mann= 4 ,-1 , 0
       0      .1       0     140     .12       0   406.6    .045       0
   508.1      .1       0
Bank Sta=406.6,508.1
XS Rating Curve= 0 ,0
Exp/Cntr(USF)=0,0
Exp/Cntr=0.3,0.1

Type RM Length L Ch R = 1 ,18454   ,274,274.8,269.2
XS GIS Cut Line= 4
1973427.34149072243005.3448316331973277.77673154 242982.17282669
1972812.23008677242965.3204594581972492.03510936242975.853188978
#Sta/Elev= 30
       0 2397.59    28.5 2388.37    45.1 2381.69    68.3 2371.23    94.9 2356.18
   151.3 2326.96   180.8 2314.61     217 2300.35   240.1 2293.59   282.6 2286.02
   294.2 2284.79     299 2284.34   443.5 2284.76   479.6 2284.47   492.7 2285.51
   512.6 2284.79   535.4 2287.24   545.3 2287.54   624.1 2287.13   679.9 2287.78
   735.7 2290.01   745.5 2292.23   759.7 2294.54   781.6 2301.04   811.2 2311.44
   856.1 2331.54   876.8 2338.55   916.5 2346.79   932.6  2349.3   937.6 2350.74
#Mann= 6 ,-1 , 0
       0     .12       0  211.35    .025       0   294.2    .045       0
   443.5      .1       0  611.35     .12       0   707.2      .1       0
Bank Sta=294.2,443.5
XS Rating Curve= 0 ,0
Exp/Cntr(USF)=0,0
Exp/Cntr=0.3,0.1

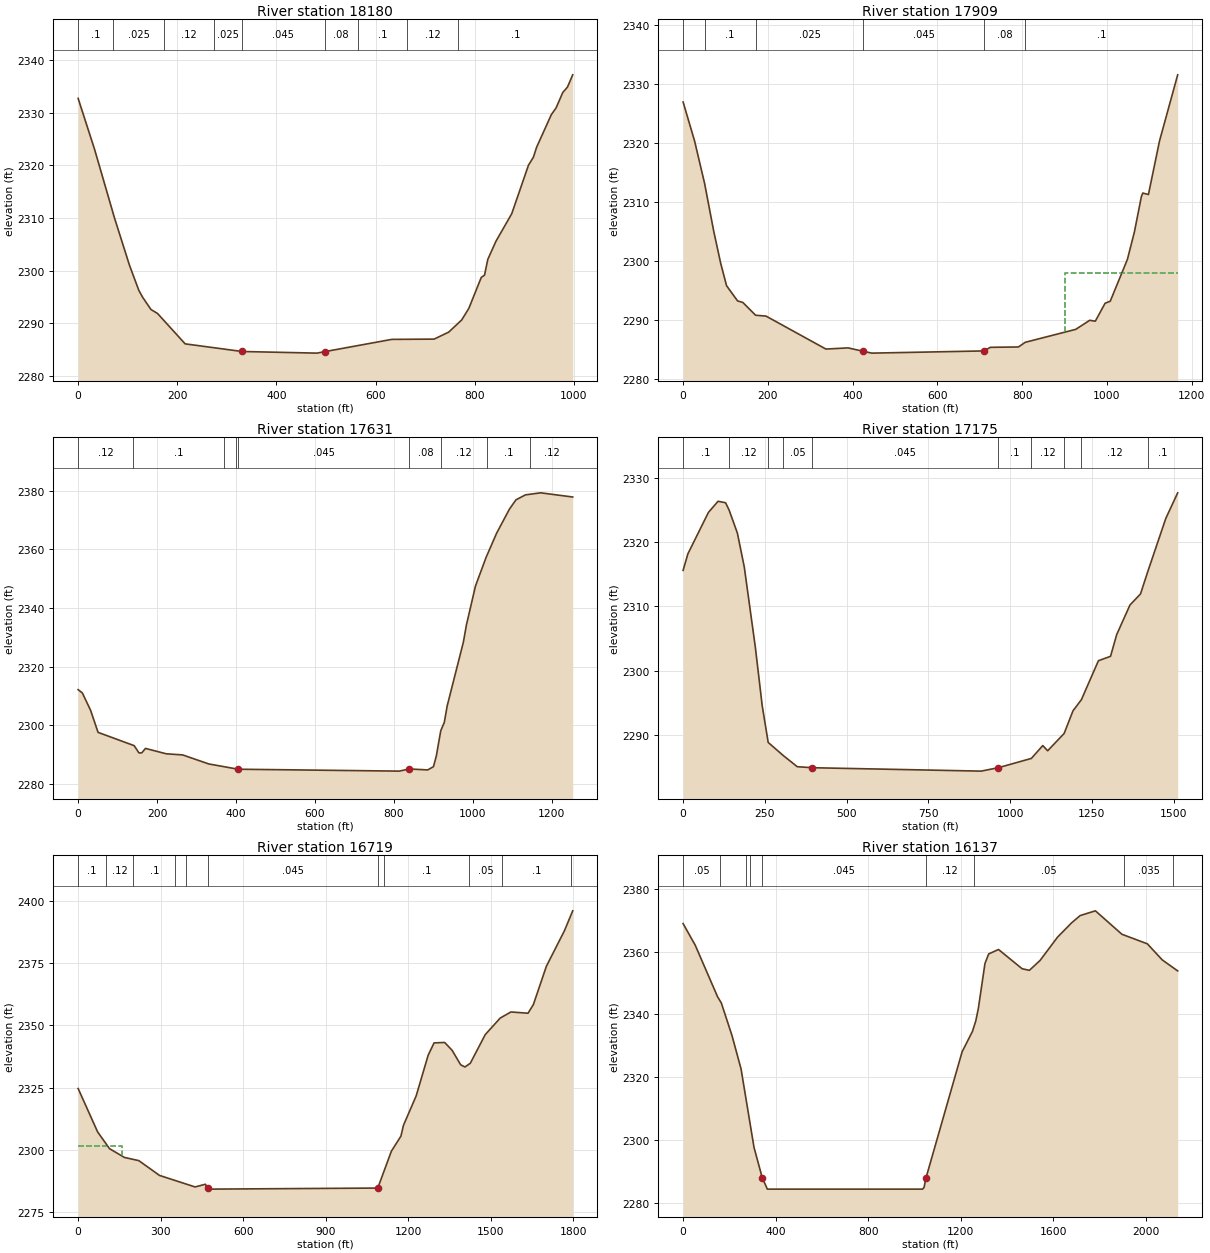
Type RM Length L Ch R = 1 ,18180   ,221,270.1,333
XS GIS Cut Line= 4
1973484.21823012242733.6004100241973353.61238408242706.215313272
1972751.14025555242699.8956755611972489.92856346 242710.42840508
#Sta/Elev= 30
       0 2332.71    33.2 2323.02    73.4 2309.98   103.6 2301.01   122.4 2296.26
   130.4  2294.9   146.9 2292.62     160 2291.88   215.8  2286.1   330.6 2284.65
   481.6 2284.34   497.2 2284.62   632.5 2286.95   717.8    2287   747.3 2288.33
   773.6 2290.65   787.9 2292.84     813 2298.72   819.6 2299.16   826.1 2302.13
   842.6 2305.59   874.4 2310.81   908.2 2320.04   918.1 2321.54   924.6 2323.44
   954.2 2329.62     964 2330.93   977.3 2333.83   986.8 2334.86   997.4 2337.19
#Mann= 9 ,-1 , 0
       0      .1       0      70    .025       0  173.45     .12       0
  273.45    .025       0   330.6    .045       0   497.2     .08       0
  563.45      .1       0  663.45     .12       0  765.95      .1       0
Bank Sta=330.6,497.2
XS Rating Curve= 0 ,0
Exp/Cntr(USF)=0,0
Exp/Cntr=0.3,0.1

Type RM Length L Ch R = 1 ,17909   ,274.3,278.6,305
XS GIS Cut Line= 4
 1973557.2451548242681.1708230821973362.27262835242547.288127852
1972730.30885717242315.5680784181972473.93766861242293.511600103
#Sta/Elev= 30
       02326.961  27.0462320.354  50.6422313.164  72.304 2305.01  88.6452299.597
 102.5532295.781 128.5082293.207 140.8072292.949 170.9812290.776  195.682290.627
 336.9432285.034 389.3592285.233   425.52284.648  445.272284.344   710.12284.718
 724.8242285.328 791.2182285.389 807.2822286.181  926.47 2288.38 959.3992289.917
 972.5712289.766 995.6222292.806 1007.832293.1571048.3092300.2551064.7742304.899
1081.2392310.8981084.5312311.5111097.9032311.2621124.0472320.3511166.9392331.575
#Mann= 6 ,-1 , 0
       0     .12       0  50.642      .1       0 170.981    .025       0
   425.5    .045       0   710.1     .08       0 807.282      .1       0
#XS Ineff= 2 , 0
                             900            2298
Permanent Ineff=
       F       F
Bank Sta=425.5,710.1
XS Rating Curve= 0 ,0
Exp/Cntr(USF)=0,0
Exp/Cntr=0.3,0.1

Type RM Length L Ch R = 1 ,17631   ,415,455.5,515.4
XS GIS Cut Line= 4
1973731.15222219242487.6026605741973516.75266131242357.698996497
  1972880.107677242032.3546846651972634.34398821241882.555864829
#Sta/Elev= 30
       0 2312.13    10.7    2311    31.4 2305.14    50.5 2297.56   142.1 2293.02
   154.1 2290.55   161.2 2290.56   170.7 2292.09   223.3 2290.25   264.8 2289.87
   331.1 2286.79   405.6 2284.99   813.8 2284.34   839.4 2285.08   885.9 2284.75
   900.6 2285.86   907.9 2289.56     919 2298.09     928 2300.96   935.3 2306.57
   976.3  2328.3     984 2334.14    1007 2347.47  1033.9 2357.23  1060.8 2365.55
  1092.9 2373.65  1109.6 2376.87  1133.8 2378.57  1172.3 2379.26  1253.5 2377.83
#Mann= 9 ,-1 , 0
       0     .12       0     140      .1       0  370.68     .05       0
  400.68    .025       0   405.6    .045       0   839.4     .08       0
  920.68     .12       0 1035.64      .1       0 1145.64     .12       0
Bank Sta=405.6,839.4
XS Rating Curve= 0 ,0
Exp/Cntr(USF)=0,0
Exp/Cntr=0.3,0.1

Type RM Length L Ch R = 1 ,17175   ,454.1,455.8,458.7
XS GIS Cut Line= 4
1974013.72126728242282.8957964351973807.96844264242116.300832055
  1973055.653169241478.4201518781972856.38592264241309.674853185
#Sta/Elev= 30
       02315.587  14.4672318.147  77.2592324.597  106.812326.342 129.8212326.113
 140.4322325.006  165.912321.395 187.0172316.117 220.7882303.653 241.8962294.504
 260.1632288.806 305.9442286.783 348.9982285.032  394.422284.875  911.412284.344
 964.1012284.8811064.8112286.3231099.7272288.3231114.6512287.5131164.9042290.198
1192.0762293.7311217.8852295.4741269.8442301.5261306.8992302.2161325.5222305.575
1366.3032310.1981398.4672311.9191422.1472315.6081475.8522323.6741512.2012327.657
#Mann= 10 ,-1 , 0
       0      .1       0 140.432     .12       0 260.163      .1       0
 305.944     .05       0  394.42    .045       0 964.101      .1       0
1064.811     .12       01164.904      .1       01217.885     .12       0
1422.147      .1       0
Bank Sta=394.42,964.101
XS Rating Curve= 0 ,0
Exp/Cntr(USF)=0,0
Exp/Cntr=0.3,0.1

Type RM Length L Ch R = 1 ,16719   ,584.9,582.7,609.2
XS GIS Cut Line= 5
1974201.68370688242093.1906262041974245.86576393241894.639223336
1974115.94794065241788.9316024311973376.31626771241145.264798447
1972999.47861156240906.522929333
#Sta/Elev= 30
       02324.689  70.8442307.288 114.0552300.569 168.316 2297.05 220.5782295.775
 295.8032289.837 425.0912285.218 462.552  2286.3 470.4272284.933 477.2812284.344
1089.0042284.7731138.3642299.5521173.1582305.6081182.2142309.9141228.5322321.738
1272.1722338.0741293.6462343.0021332.144 2343.171359.2342340.0071390.3052334.206
 1405.842333.346 1425.262334.8281479.6332346.3341534.0072352.9611572.8452355.398
1634.987  2354.91654.4062358.3471701.7352373.7281767.0372387.9121797.4872395.968
#Mann= 11 ,-1 , 0
       0      .1       0     100     .12       0     200      .1       0
  353.41     .12       0   390.9    .025       0 470.427    .045       0
1089.004    .025       0  1110.9      .1       0 1421.39     .05       0
 1541.39      .1       0 1791.39     .05       0
#XS Ineff= 2 , 0
          160.46 2301.72
Permanent Ineff=
       F       F
Bank Sta=470.427,1089.004
XS Rating Curve= 0 ,0
Exp/Cntr(USF)=0,0
Exp/Cntr=0.3,0.1

Type RM Length L Ch R = 1 ,16137   ,482.6,605.6,498.8
XS GIS Cut Line= 4
1974808.93696196241684.3966185751974598.28237156241486.381303604
1973966.31860038240860.7371701311973201.64243724240279.330500641
#Sta/Elev= 30
       0 2368.97    52.6 2362.06   148.9 2345.67   165.2 2343.69   211.6 2333.24
   250.7 2322.61   306.7 2297.62   342.1 2288.01   364.3 2284.34  1035.8 2284.34
  1042.2 2284.91  1049.8 2287.75  1206.6  2328.1  1251.2 2334.59  1265.7 2337.93
  1276.7 2341.85  1305.5 2356.27  1321.6  2359.3    1364 2360.72  1466.3 2354.58
  1497.5 2354.07  1543.9 2357.23  1619.2 2364.64  1680.6 2369.24  1717.3 2371.53
  1783.1 2373.04  1897.8 2365.57  2007.9 2362.52  2072.1 2357.41    2139 2353.89
#Mann= 9 ,-1 , 0
       0     .05       0     160     .12       0     270      .1       0
  289.11    .025       0   342.1    .045       0  1049.8     .12       0
 1258.39     .05       0 1908.39    .035       0 2118.39     .08       0
Bank Sta=342.1,1049.8
XS Rating Curve= 0 ,0
Exp/Cntr(USF)=0,0
Exp/Cntr=0.3,0.1

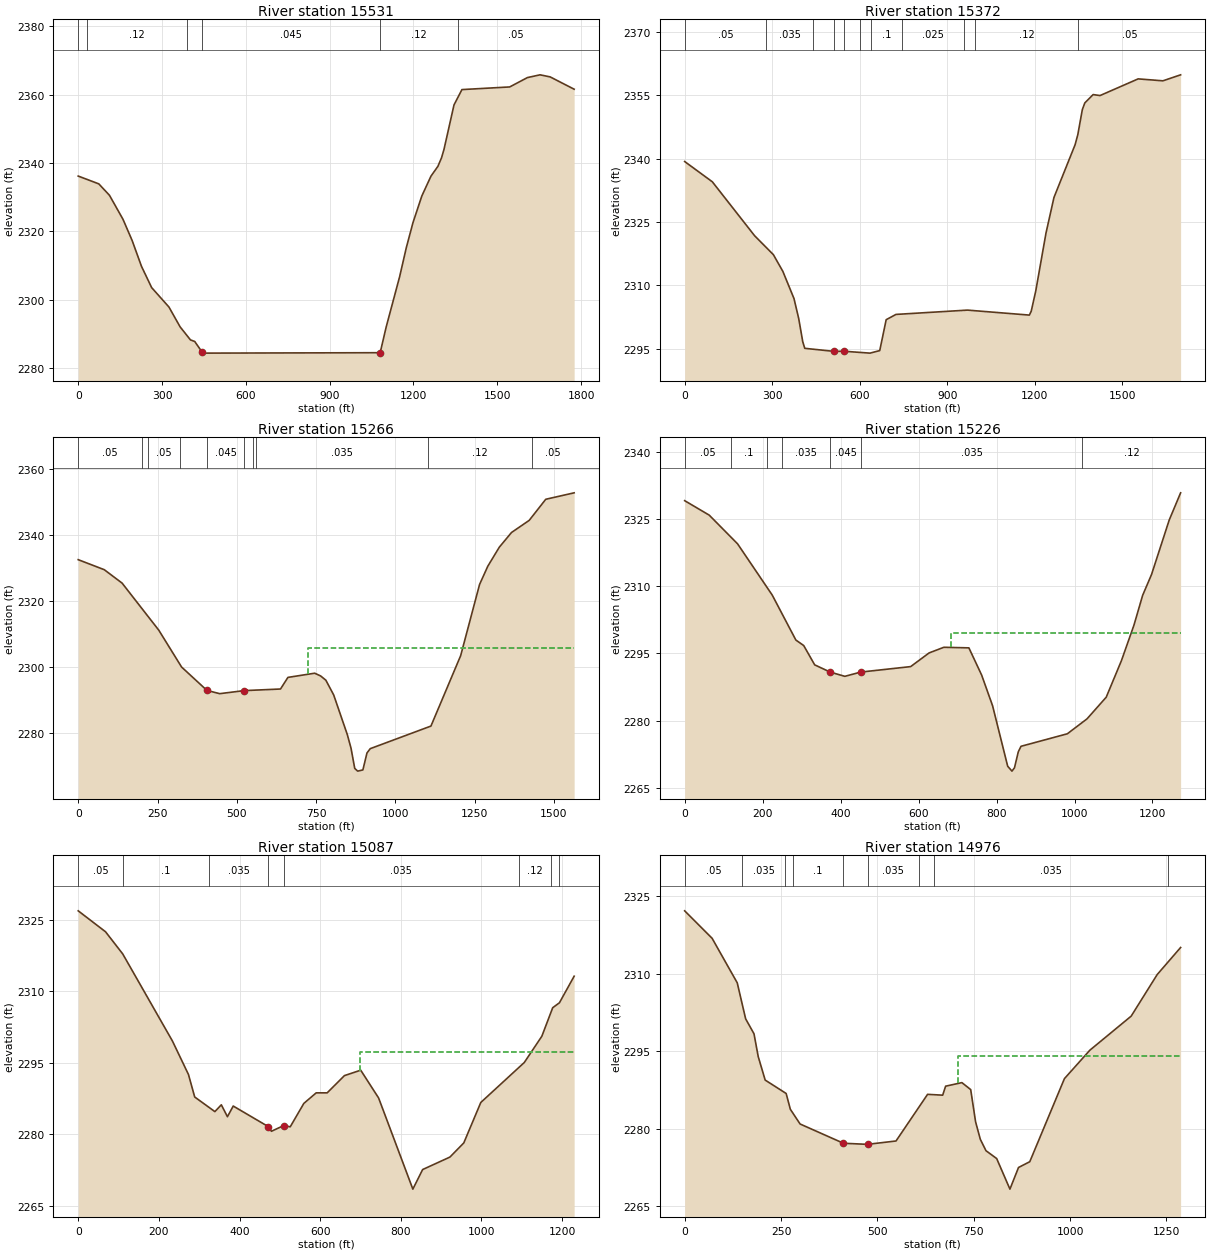
Type RM Length L Ch R = 1 ,15531   ,308.3,159.6,237.3
XS GIS Cut Line= 5
1975113.39031902241423.7890354361974952.54360641241209.806558425
1974698.18407208240795.3658616141974207.37025585240461.203325654
1973866.08637864240203.967785474
#Sta/Elev= 30
       02336.183  73.6122333.907 111.8342330.563  160.252323.535 193.0842317.306
 226.4992309.759 262.858 2303.53  324.752297.841 364.6322292.045 401.7392288.219
 417.1372287.748 444.0842284.562  446.172284.3441080.8392284.4671102.0912291.929
1150.5782306.7671174.392 2315.231198.2062322.5521229.9582330.3661262.6632336.167
1287.3812339.0281300.4452341.5331309.3392344.0351345.0612357.0151373.4422361.506
1544.4562362.2811607.9042365.0231653.0962365.8281689.2092365.2251775.1052361.617
#Mann= 6 ,-1 , 0
       0     .05       0      30     .12       0  387.69     .05       0
 444.084    .045       01080.839     .12       0 1357.74     .05       0
Bank Sta=444.084,1080.839
XS Rating Curve= 0 ,0
Exp/Cntr(USF)=0,0
Exp/Cntr=0.3,0.1

Type RM Length L Ch R = 1 ,15372   ,126.7,105.9,483.4
XS GIS Cut Line= 6
1975258.24962197241323.2207989111974865.02912143240812.942854228
1974842.86492581 240761.001840111974831.61095775240753.332075759
1974486.71634851240511.2325972521974010.88933591 240207.49956492
#Sta/Elev= 30
       0 2339.32    94.8 2334.52   239.9 2321.73   304.2 2317.25   336.7 2313.28
   374.8 2306.85     391  2302.1   404.8 2296.63   411.7 2295.07   511.22294.349
     5462294.376   635.3 2293.93   668.7 2294.53   690.8 2301.85   724.4  2303.1
   969.5 2304.12  1181.7 2302.94  1188.1 2303.87  1203.7  2308.7  1238.7 2322.38
    1266  2330.8  1338.5 2343.31  1347.7 2345.67  1363.3 2351.63  1371.8 2353.21
  1400.3 2355.18    1424 2354.95  1554.7  2358.9  1639.6 2358.44  1700.2 2359.86
#Mann= 11 ,-1 , 0
       0     .05       0     280    .035       0     440      .1       0
   511.2    .045       0     546    .025       0     600    .035       0
     640      .1       0  746.06    .025       0  956.06    .035       0
  996.06     .12       0 1349.35     .05       0
Bank Sta=511.2,546
XS Rating Curve= 0 ,0
Exp/Cntr(USF)=0,0
Exp/Cntr=0.3,0.1

Type RM Length L Ch R = 1 ,15266   ,35.6,39.5,43.5
XS GIS Cut Line= 4
1975316.04237654241265.4280443451974850.81070228240641.266295027
1974636.97751038240470.7776690561974186.51509562240228.048099877
#Sta/Elev= 30
       0 2332.55    82.1 2329.52   138.4 2325.46   253.9 2311.24   325.9 2300.08
  405.79 2293.01     446 2292.02   522.8 2292.94   637.8 2293.43   661.2 2296.94
   745.6 2298.21   764.4 2297.37   780.8 2296.09   805.5 2291.63   848.5 2279.62
   860.2  2275.5   871.8 2269.42   881.1 2268.59   897.5 2268.95   910.4 2274.08
   920.8 2275.39  1112.1 2282.22  1205.8 2303.52  1265.4 2325.05  1291.3 2330.56
  1327.6 2336.32    1366 2340.76  1421.9 2344.44  1474.1 2350.82  1563.6 2352.77
#Mann= 10 ,-1 , 0
       0     .05       0     200      .1       0     220     .05       0
     320    .035       0  405.79    .045       0   522.8    .035       0
     550    .025       0     560    .035       0 1101.95     .12       0
 1431.95     .05       0
#XS Ineff= 2 , 0
                          724.36         2305.92
Permanent Ineff=
       F       F
Bank Sta=405.79,522.8
XS Rating Curve= 0 ,0
Exp/Cntr(USF)=0,0
Exp/Cntr=0.3,0.1

Type RM Length L Ch R = 1 ,15226   ,153.1,139.3,101.6
XS GIS Cut Line= 5
1975310.17449582241209.0468780981975118.21550032240941.839956364
1974907.82844125240630.098547673  1974705.119742240430.461192354
1974442.51983616240326.035498803
#Sta/Elev= 30
       0 2329.07      63 2325.84   135.7 2319.44   224.6 2308.01   285.2 2297.98
   305.4 2296.74   333.5 2292.44   373.1 2290.83   410.8 2289.88   451.9 2290.83
   579.7 2292.05     627  2295.1   664.8 2296.36   729.1 2296.23   761.8 2290.16
   789.9  2283.3   828.6 2269.82   839.6 2268.73     846 2269.47   855.8 2273.04
   862.8 2274.27   981.6 2277.06  1032.1 2280.39  1081.4 2285.23  1120.4 2293.38
  1152.4 2301.27  1174.8 2307.95  1197.6  2312.6    1243 2324.76  1272.2 2330.82
#Mann= 7 ,-1 , 0
       0     .05       0     120      .1       0     210     .05       0
     250    .035       0   373.1    .045       0   451.9    .035       0
 1019.61     .12       0
#XS Ineff= 2 , 0
                          681.95         2299.56
Permanent Ineff=
       F       F
Bank Sta=373.1,451.9
XS Rating Curve= 0 ,0
Exp/Cntr(USF)=0,0
Exp/Cntr=0.3,0.1

Type RM Length L Ch R = 1 ,15087   ,113.3,110.5,101.5
XS GIS Cut Line= 5
1975331.74272026241185.626351221  1975215.031651240936.847493055
1974978.53816854240563.6792058061974780.43648519240357.899162632
1974557.76405041240310.293331748
#Sta/Elev= 30
       0 2326.91    67.8 2322.51   110.4 2317.86   233.6 2299.58   273.4 2292.54
   288.9 2287.81   338.9 2284.74   354.9 2286.17   370.1 2283.67   384.4 2285.91
   471.4 2281.59   479.2 2280.61   509.8 2281.82   525.8 2281.55   559.6 2286.47
   590.2 2288.68   617.4 2288.68   660.2  2292.3   700.6 2293.44     745  2287.6
   829.9 2268.46   854.1 2272.57   921.8 2275.19   956.2 2278.16   998.4 2286.66
  1106.2 2295.05  1149.8 2300.57  1176.7 2306.56  1193.4  2307.6  1229.9 2313.18
#Mann= 8 ,-1 , 0
       0     .05       0     110      .1       0   324.8    .035       0
   471.4    .045       0   509.8    .035       0 1092.23     .12       0
 1172.23    .035       0 1192.23     .12       0
#XS Ineff= 2 , 0
                          697.99         2297.24
Permanent Ineff=
       F       F
Bank Sta=471.4,509.8
XS Rating Curve= 0 ,0
Exp/Cntr(USF)=0,0
Exp/Cntr=0.3,0.1

Type RM Length L Ch R = 1 ,14976   ,102.9,105.4,95.4
XS GIS Cut Line= 5
1975405.38377075241146.877332616 1975274.7779247240868.813273293
 1975059.9102425240533.8724745631974853.46874391240344.283343207
1974560.65886326240272.660782472
#Sta/Elev= 30
       0 2322.22    71.2  2316.9   136.4 2308.28   158.2 2301.31   179.9 2298.41
   190.8 2294.01   208.9 2289.45   263.3 2286.86   274.2  2283.8   299.5 2280.95
     412 2277.22   474.4 2277.01   548.4 2277.66   630.3 2286.69   669.5 2286.53
   677.1 2288.27   719.3 2288.96   742.2 2287.61   754.9 2281.36   767.2 2277.98
   781.8 2275.78   809.6 2274.26     844 2268.34   866.3 2272.53   895.5 2273.65
   985.4 2289.73  1051.3 2295.23  1158.6 2301.83  1226.1 2309.88  1286.9 2315.12
#Mann= 9 ,-1 , 0
       0     .05       0     150    .035       0     260     .08       0
     280      .1       0     412    .045       0   474.4    .035       0
  607.21      .1       0  647.21    .035       0 1255.44     .12       0
#XS Ineff= 2 , 0
                          710.03         2294.15
Permanent Ineff=
       F       F
Bank Sta=412,474.4
XS Rating Curve= 0 ,0
Exp/Cntr(USF)=0,0
Exp/Cntr=0.3,0.1

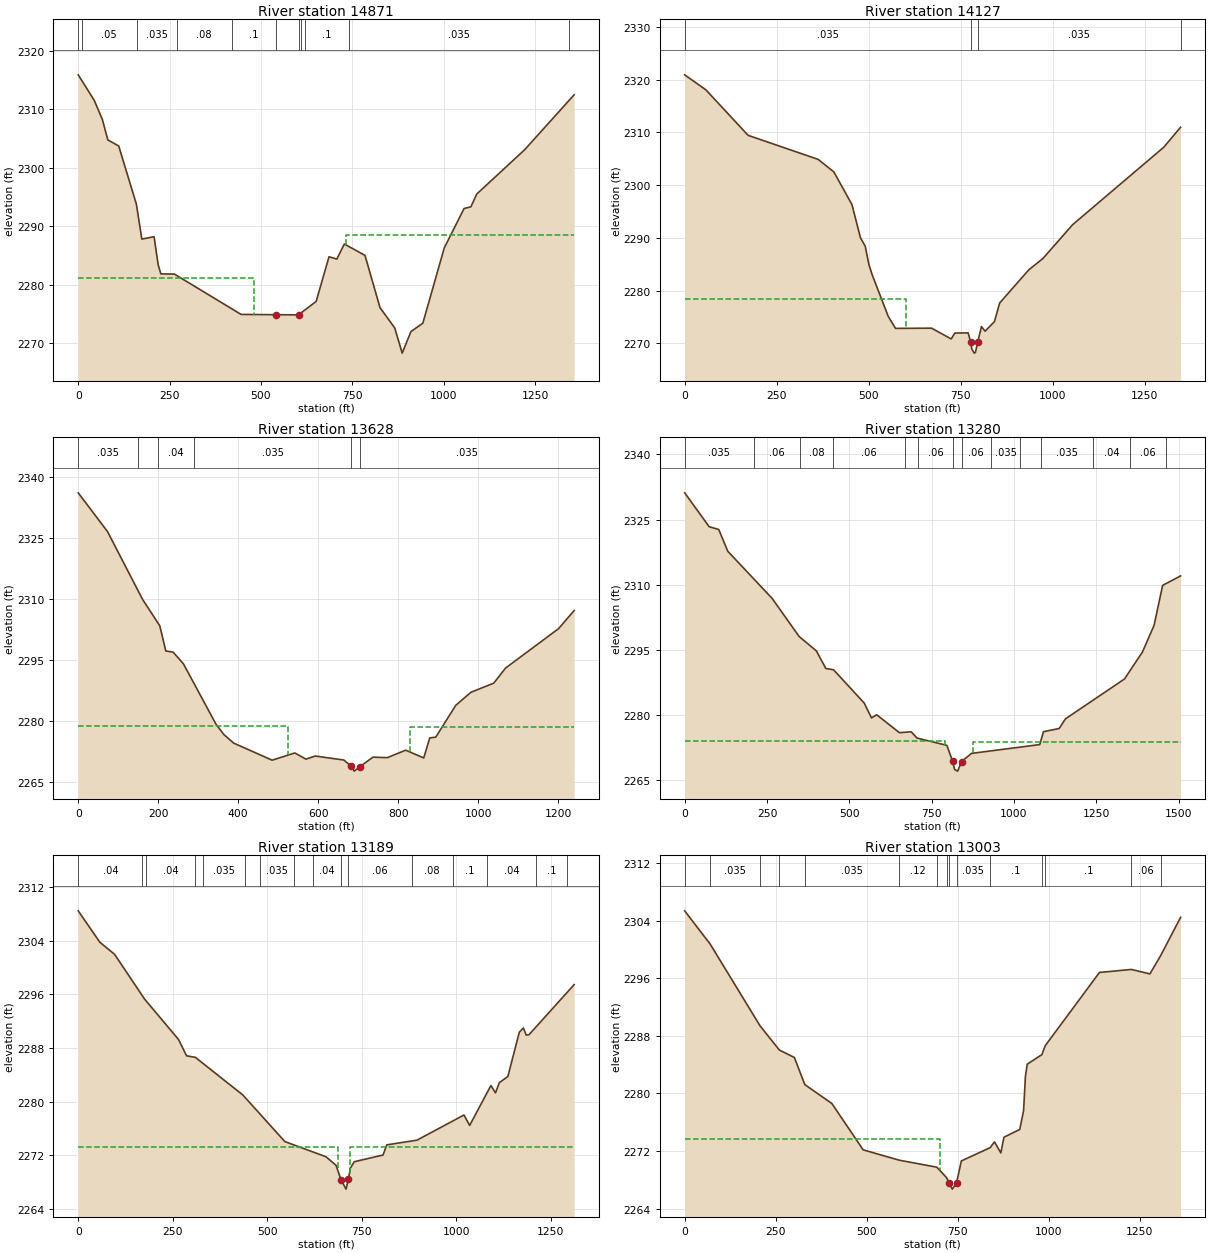
Type RM Length L Ch R = 1 ,14871   ,711.7,744.5,568.6
XS GIS Cut Line= 4
1975485.14290723241150.6163512991975225.78497554240666.026531555
 1974961.3081373240346.9480234841974580.42357241240249.794126394
#Sta/Elev= 30
       0 2315.88    43.8 2311.53    66.2 2308.23      81 2304.75   110.8 2303.72
   159.2 2293.76   174.1 2287.79   207.6  2288.2   218.7 2283.43   226.2 2281.84
   263.2 2281.81   445.7 2274.91   541.9 2274.86   602.8 2274.83   651.1 2277.13
   686.3 2284.77   707.7 2284.37   728.2 2286.95   784.8    2285   825.9 2276.06
   866.1  2272.6   886.6 2268.29   910.4 2271.97     943  2273.4  1001.7 2286.29
  1055.9 2293.02  1074.5 2293.31  1090.7  2295.5  1221.8 2303.08  1357.1 2312.47
#Mann= 11 ,-1 , 0
       0      .1       0      10     .05       0     160    .035       0
     270     .08       0     420      .1       0   541.9    .045       0
   602.8      .1       0  609.63    .035       0  619.63      .1       0
  739.63    .035       0 1344.07     .12       0
#XS Ineff= 2 , 0
          482.04 2281.17   734.1         2288.48
Permanent Ineff=
       F       F
Bank Sta=541.9,602.8
XS Rating Curve= 0 ,0
Exp/Cntr(USF)=0,0
Exp/Cntr=0.3,0.1

Type RM Length L Ch R = 1 ,14127   ,497.6,498.7,446.6
XS GIS Cut Line= 4
1975933.90038115240150.7232725311975439.07274831240150.723272531
1975026.14762022240183.143013993 1974590.6613855240236.438625363
#Sta/Elev= 30
       0  2320.9    57.7 2318.05   172.4 2309.43   362.8 2304.87   405.4  2302.5
   454.6 2296.31   477.6 2290.04   490.8 2288.39   500.6 2284.96   509.3 2283.06
   553.2 2275.12     573 2272.84     671 2272.88   724.4 2270.84   734.2 2271.95
   770.4 2271.99     777  2270.3   780.3 2268.94   786.8 2268.15   790.2 2268.29
   796.1 2270.18   806.6 2273.18   816.5 2272.31   841.9 2274.13     856 2277.65
   935.1 2283.93   973.8  2286.1  1054.1 2292.48    1302 2307.18  1347.8 2310.97
#Mann= 4 ,-1 , 0
       0    .035       0     777    .045       0   796.1    .035       0
 1347.76     .12       0
#XS Ineff= 2 , 0
          601.24  2278.5
Permanent Ineff=
       F       F
Bank Sta=777,796.1
XS Rating Curve= 0 ,0
Exp/Cntr(USF)=0,0
Exp/Cntr=0.3,0.1

Type RM Length L Ch R = 1 ,13628   ,337.8,347.7,327.3
XS GIS Cut Line= 4
1975594.34624689239500.6221411141975224.07867336239841.882577553
1975032.97282895240026.1632132311974600.28830028240211.749907369
#Sta/Elev= 30
       0 2336.13    73.3  2326.6     161 2309.92     204 2303.43     219 2297.25
   237.3 2296.97   262.9 2294.12   344.1 2279.32   363.7 2276.75   388.5 2274.62
   484.8 2270.41   541.5 2272.19   569.3 2270.67   592.5 2271.43   664.1 2270.45
     683 2268.86     690 2267.72   703.9 2268.81     737 2271.16   772.5 2271.03
   818.8 2272.87   863.8 2270.96   878.8 2275.89   893.8 2276.07   943.8 2283.89
   981.7  2287.1  1038.7 2289.34  1068.3 2293.05  1200.9 2302.75  1239.8  2307.2
#Mann= 6 ,-1 , 0
       0    .035       0     150     .06       0     200     .04       0
     290    .035       0     683    .045       0   703.9    .035       0
#XS Ineff= 2 , 0
           523.5 2278.72  828.37         2278.54
Permanent Ineff=
       F       F
Bank Sta=683,703.9
XS Rating Curve= 0 ,0
Exp/Cntr(USF)=0,0
Exp/Cntr=0.5,0.3

Type RM Length L Ch R = 1 ,13280   ,83.3,91.1,95.8
XS GIS Cut Line= 4
1975655.50820347239245.8727192541975152.71123874239589.739608925
1974886.86456773239904.7101213121974456.30854621240127.212226393
#Sta/Elev= 30
       0 2331.17    74.3 2323.38   103.4 2322.74     131 2317.72   265.6 2306.88
   347.5 2298.12   399.8 2294.81   428.8 2290.75     452 2290.47   545.1 2282.81
   567.3 2279.39   583.2 2280.11     652 2275.99   687.8 2276.19   705.6 2274.75
   796.4 2273.07  813.74 2269.37   819.7 2267.52     829 2267.14   840.9 2269.35
   870.9 2271.22  1078.3 2273.25  1089.4  2276.2  1137.4 2276.96  1156.2 2279.16
  1335.5 2288.34    1390 2294.53  1425.5  2300.7  1451.3 2309.87    1506 2312.06
#Mann= 14 ,-1 , 0
       0    .035       0     210     .06       0     350     .08       0
     450     .06       0  669.14     .08       0  709.14     .06       0
  813.74    .045       0   840.9     .06       0  929.14    .035       0
 1019.14     .08       0  1081.3    .035       0  1241.3     .04       0
  1351.3     .06       0  1461.3     .04       0
#XS Ineff= 2 , 0
          791.15 2274.05  874.56         2273.94
Permanent Ineff=
       F       F
Bank Sta=813.74,840.9
XS Rating Curve= 0 ,0
Exp/Cntr(USF)=0,0
Exp/Cntr=0.5,0.3

Type RM Length L Ch R = 1 ,13189   ,191.7,186.5,176.4
XS GIS Cut Line= 4
1975409.88899656239216.9763419711974988.60897221239674.664963698
1974848.69219327239802.6376273631974410.17253245240043.226235053
#Sta/Elev= 30
       0 2308.49    57.4 2303.79    96.3 2301.99   175.2 2295.34   265.7 2289.25
   286.6 2286.84   309.9 2286.61   435.3    2281   546.7 2274.03   655.2 2271.77
   681.9  2270.5   695.3 2268.32   708.5 2266.93   714.9 2268.45   719.7 2270.04
   730.1 2271.02   806.3 2272.02   816.2 2273.54     896 2274.24  1020.5    2278
  1035.5 2276.44  1091.7  2282.4  1103.8 2281.31    1114 2282.83  1136.5 2283.74
  1166.9 2290.37  1177.7    2291  1185.1 2289.93  1192.6    2290  1311.9 2297.47
#Mann= 16 ,-1 , 0
       0     .04       0     170     .06       0     180     .04       0
     310     .06       0     330    .035       0     440     .06       0
     480    .035       0     570     .06       0     620     .04       0
   695.3    .045       0   714.9     .06       0  881.67     .08       0
  991.67      .1       0 1081.67     .04       0 1211.67      .1       0
 1291.67     .04       0
#XS Ineff= 2 , 0
          687.03 2273.27  717.71         2273.29
Permanent Ineff=
       F       F
Bank Sta=695.3,714.9
XS Rating Curve= 0 ,0
Exp/Cntr(USF)=0,0
Exp/Cntr=0.5,0.3

Type RM Length L Ch R = 1 ,13003   ,179.1,181.9,182.6
XS GIS Cut Line= 4
1975325.73851386239172.9963735631974931.55333225239539.725870882
 1974555.0182334239865.2718417641974251.04458589239982.939060155
#Sta/Elev= 30
       0  2305.4    70.1 2300.77   207.1  2289.4   260.1 2286.04   301.2 2285.01
   330.1 2281.23   404.2 2278.61   490.3 2272.16   589.7 2270.72   692.6 2269.75
   719.42268.289  726.09 2267.57   735.1  2266.7   746.8 2267.59   759.8 2270.62
   839.1 2272.47   850.9 2273.27   868.3 2271.74   876.9 2273.92   920.3    2275
   930.8 2277.61   935.8 2282.35   940.8 2284.07     981  2285.4   990.3 2286.65
  1139.2 2296.83  1226.9 2297.25  1277.8 2296.63  1307.6  2299.2  1362.1  2304.5
#Mann= 15 ,-1 , 0
       0     .04       0    70.1    .035       0   207.1      .1       0
   260.1     .04       0   330.1    .035       0   589.7     .12       0
   692.6      .1       0   719.4    .035       0  726.09    .045       0
   746.8    .035       0   839.1      .1       0     981     .12       0
   990.3      .1       0  1226.9     .06       0  1307.6     .04       0
#XS Ineff= 2 , 0
             700 2273.74
Permanent Ineff=
       F       F
Bank Sta=726.09,746.8
XS Rating Curve= 0 ,0
Exp/Cntr(USF)=0,0
Exp/Cntr=0.3,0.1