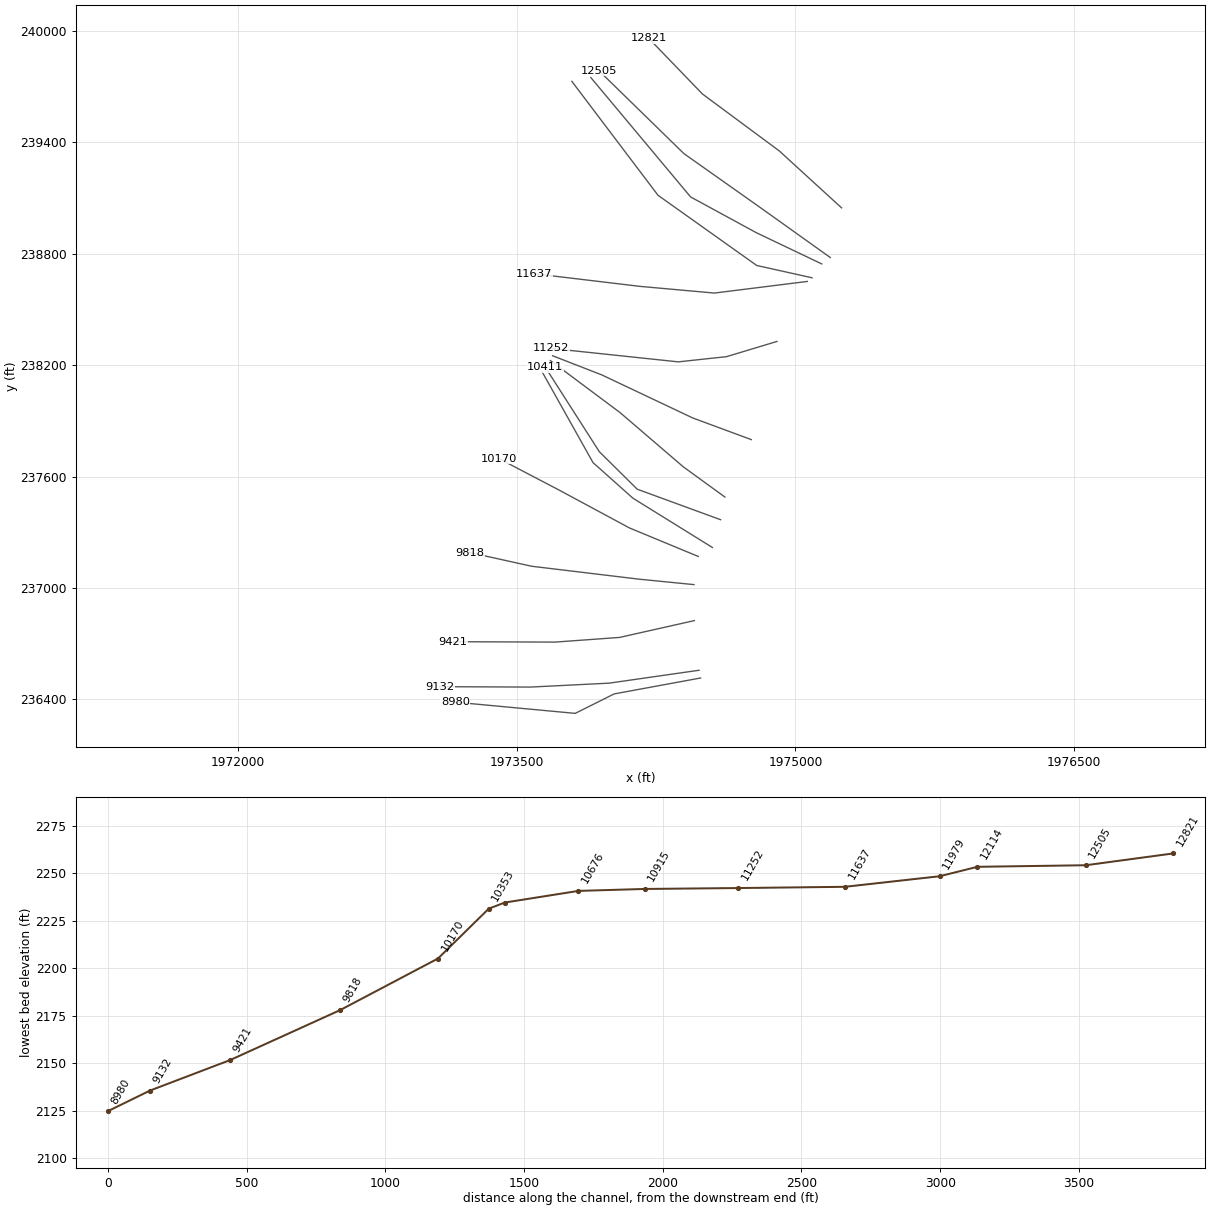
HEC-RAS study JUMPNGBR.prj: JUMPNGBR

--- JUMPNGBR.g01 (geometry) --- (continued)

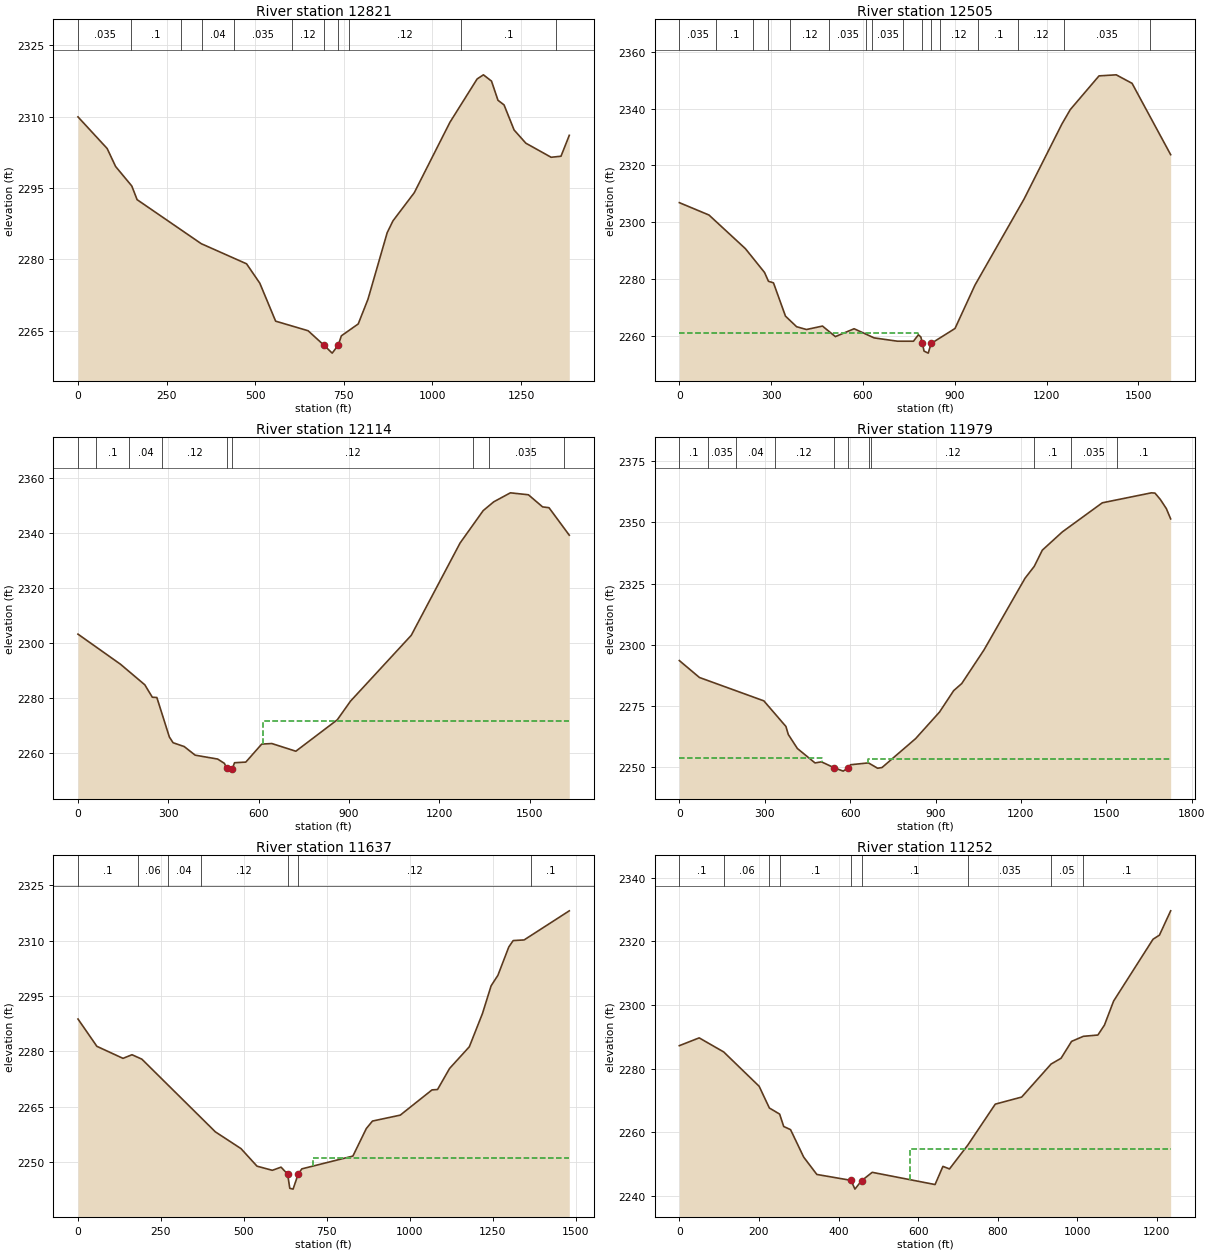
Type RM Length L Ch R = 1 ,12821   ,314.5,316,316.3
XS GIS Cut Line= 4
1975247.96652678239047.5660530671974912.62585214239354.367095828
1974498.80118981239661.1681385881974209.83741697239960.834273377
#Sta/Elev= 30
       0 2309.94    82.3  2303.3   106.2 2299.52   151.8 2295.43   166.8 2292.56
   347.7 2283.32   475.6 2279.09   512.9 2275.03   557.6 2267.05   649.2 2265.04
  693.682262.018   717.1 2260.34   734.32262.017     743 2263.97   790.6 2266.47
   818.1 2271.66   872.3 2285.63   888.6 2288.11   948.7 2294.02  1049.4 2308.82
    1126  2317.9  1143.8 2318.77  1166.6 2317.45  1184.8 2313.43    1202 2312.45
  1230.3 2307.19  1263.4 2304.42  1334.8 2301.46  1362.6 2301.68    1386 2306.07
#Mann= 11 ,-1 , 0
       0    .035       0     150      .1       0     290     .06       0
     350     .04       0     440    .035       0  604.51     .12       0
  693.68    .045       0   734.3      .1       0  764.51     .12       0
 1079.66      .1       0 1349.66     .04       0
Bank Sta=693.68,734.3
XS Rating Curve= 0 ,0
Exp/Cntr(USF)=0,0
Exp/Cntr=0.3,0.1

Type RM Length L Ch R = 1 ,12505   ,382.2,390.4,368.3
XS GIS Cut Line= 4
1975187.31980903238780.0070041481974812.73714054239047.566053067
1974398.91247821239340.0972798851973942.27836806239786.029028084
#Sta/Elev= 30
       0 2306.95    96.8 2302.61   215.9 2290.79   278.3 2282.45   291.2 2279.34
   307.6 2278.79   346.8 2267.11   383.1 2263.39   415.3 2262.41   467.7 2263.62
   509.8 2259.92   571.1 2262.68   636.5 2259.47   712.4 2258.31     765  2258.3
   781.1 2260.56   789.2 2259.77  794.342257.504   799.5 2254.83   813.3 2254.12
  822.622257.501   900.7 2262.77   965.9 2277.99  1126.7 2308.28  1250.1 2334.57
  1277.3 2339.61  1371.3 2351.46  1427.6 2351.83  1479.3 2348.84  1605.4  2323.8
#Mann= 16 ,-1 , 0
       0    .035       0     120      .1       0     240     .04       0
     290     .06       0     360     .12       0  490.33    .035       0
  610.33     .12       0  630.33    .035       0  730.33     .12       0
  794.34    .045       0  822.62      .1       0  850.33     .12       0
  977.11      .1       0 1107.11     .12       0 1257.11    .035       0
 1537.11      .1       0
#XS Ineff= 2 , 0
          779.79  2261.3
Permanent Ineff=
       F       F
Bank Sta=794.34,822.62
XS Rating Curve= 0 ,0
Exp/Cntr(USF)=0,0
Exp/Cntr=0.3,0.1

Type RM Length L Ch R = 1 ,12114   ,137.9,135.7,132
XS GIS Cut Line= 4
1975141.39320505238745.4721467421974788.39154988238914.128493102
 1974435.3898947239106.3182831411973898.04293072239749.565743679
#Sta/Elev= 30
       0 2303.24     141 2292.28   221.9 2284.77   246.9 2280.23   261.9 2280.14
   303.4 2265.74   315.7 2263.65   352.7 2262.25   389.1 2259.11   463.8 2257.69
   486.3 2256.11   493.6 2254.26   507.2 2253.29   512.3 2254.14   519.8 2256.35
   557.2 2256.58   610.1 2263.15   643.6 2263.35   723.4 2260.55     861 2272.01
   904.8  2278.8  1106.6 2302.81  1268.7 2336.47  1345.5 2348.29  1380.5 2351.49
  1435.8 2354.77  1495.6 2354.06  1542.6 2349.65    1564 2349.34  1631.3 2339.32
#Mann= 9 ,-1 , 0
       0    .035       0      60      .1       0     170     .04       0
     280     .12       0   493.6    .045       0   512.3     .12       0
 1313.15      .1       0 1363.15    .035       0 1613.15      .1       0
#XS Ineff= 2 , 0
                          614.91         2271.49
Permanent Ineff=
       F       F
Bank Sta=493.6,512.3
XS Rating Curve= 0 ,0
Exp/Cntr(USF)=0,0
Exp/Cntr=0.3,0.1

Type RM Length L Ch R = 1 ,11979   ,328,341.8,354.6
XS GIS Cut Line= 4
1975088.77706928238670.9067731831974791.33241663238737.197556321
1974259.78177277239115.3476787931973796.01275465239728.949764314
#Sta/Elev= 30
       0 2293.54    70.5 2286.63   296.9 2277.07   374.5 2266.59   382.7 2263.34
   414.7 2257.59   476.8 2251.69   499.3 2252.14  542.422249.788   575.8 2248.34
  593.432249.747   601.5 2250.95   664.4 2251.71   696.6 2249.52   712.1 2249.81
   830.1 2261.63     914 2272.48   963.8 2281.25   992.3 2284.17  1070.5 2297.92
  1214.4 2327.18  1247.1 2332.09  1275.3 2338.69  1345.6 2346.15  1486.1 2358.05
  1658.6 2362.13  1671.2 2362.01  1689.9 2359.42    1711 2355.69  1726.2 2351.47
#Mann= 11 ,-1 , 0
       0      .1       0     100    .035       0     200     .04       0
  334.74     .12       0  542.42    .045       0  593.43     .12       0
  664.74      .1       0  674.74     .12       0 1247.08      .1       0
 1377.08    .035       0 1537.08      .1       0
#XS Ineff= 2 , 0
          501.18 2253.63  662.48         2253.25
Permanent Ineff=
       F       F
Bank Sta=542.42,593.43
XS Rating Curve= 0 ,0
Exp/Cntr(USF)=0,0
Exp/Cntr=0.3,0.1

Type RM Length L Ch R = 1 ,11637   ,378.8,384.7,388.8
XS GIS Cut Line= 4
1975063.38496856238651.1414790671974562.86966178238588.577065719
1974162.83659462238624.5990006771973592.17330924238692.851087965
#Sta/Elev= 30
       0 2288.78      57 2281.39   135.7 2278.14   162.8 2279.12   192.6 2277.92
   414.1 2258.26   491.3 2253.73   539.6 2248.98   585.7 2247.86   612.1 2248.71
  631.822246.826   638.4 2242.99   648.3 2242.77  663.632246.825   674.7 2248.25
   828.6 2251.71     869 2259.15   887.6 2261.18   971.3 2262.78  1067.1 2269.61
  1083.7 2269.71    1120 2275.41  1179.5 2281.27  1219.1 2290.26  1245.2 2297.76
  1265.8 2300.62  1298.4 2308.25  1311.7 2309.99  1344.7 2310.17  1480.8 2318.04
#Mann= 7 ,-1 , 0
       0      .1       0     180     .06       0     270     .04       0
     370     .12       0  631.82    .045       0  663.63     .12       0
 1366.06      .1       0
#XS Ineff= 2 , 0
                          708.88         2251.21
Permanent Ineff=
       F       F
Bank Sta=631.82,663.63
XS Rating Curve= 0 ,0
Exp/Cntr(USF)=0,0
Exp/Cntr=0.3,0.1

Type RM Length L Ch R = 1 ,11252   ,347.2,337.5,326.5
XS GIS Cut Line= 4
1974900.26809739238327.9271192041974628.75773644238246.005889606
1974368.95040829238217.9186108871973683.15268622238290.477414245
#Sta/Elev= 30
       0 2287.21    49.8 2289.66   111.4 2285.24   200.5 2274.45   226.2 2267.62
     252  2265.7   262.2 2261.81   279.4 2260.82   312.5 2252.17   345.5 2246.73
   431.3 2244.88   441.2 2242.12   457.7 2244.75   484.6  2247.4   642.5 2243.56
   662.3 2249.27   678.8 2248.47     725    2256   793.8 2268.83   860.2 2271.06
     934 2281.43   959.2 2283.26   985.5 2288.56  1015.2 2290.15  1051.6 2290.55
  1068.1 2293.67  1091.2 2301.24  1190.2 2320.66  1206.3 2321.95  1234.5 2329.59
#Mann= 9 ,-1 , 0
       0      .1       0   111.4     .06       0   226.2     .05       0
     252      .1       0   431.3    .045       0   457.7      .1       0
     725    .035       0     934     .05       0  1015.2      .1       0
#XS Ineff= 2 , 0
                             580         2254.79
Permanent Ineff=
       F       F
Bank Sta=431.3,457.7
XS Rating Curve= 0 ,0
Exp/Cntr(USF)=0,0
Exp/Cntr=0.3,0.1

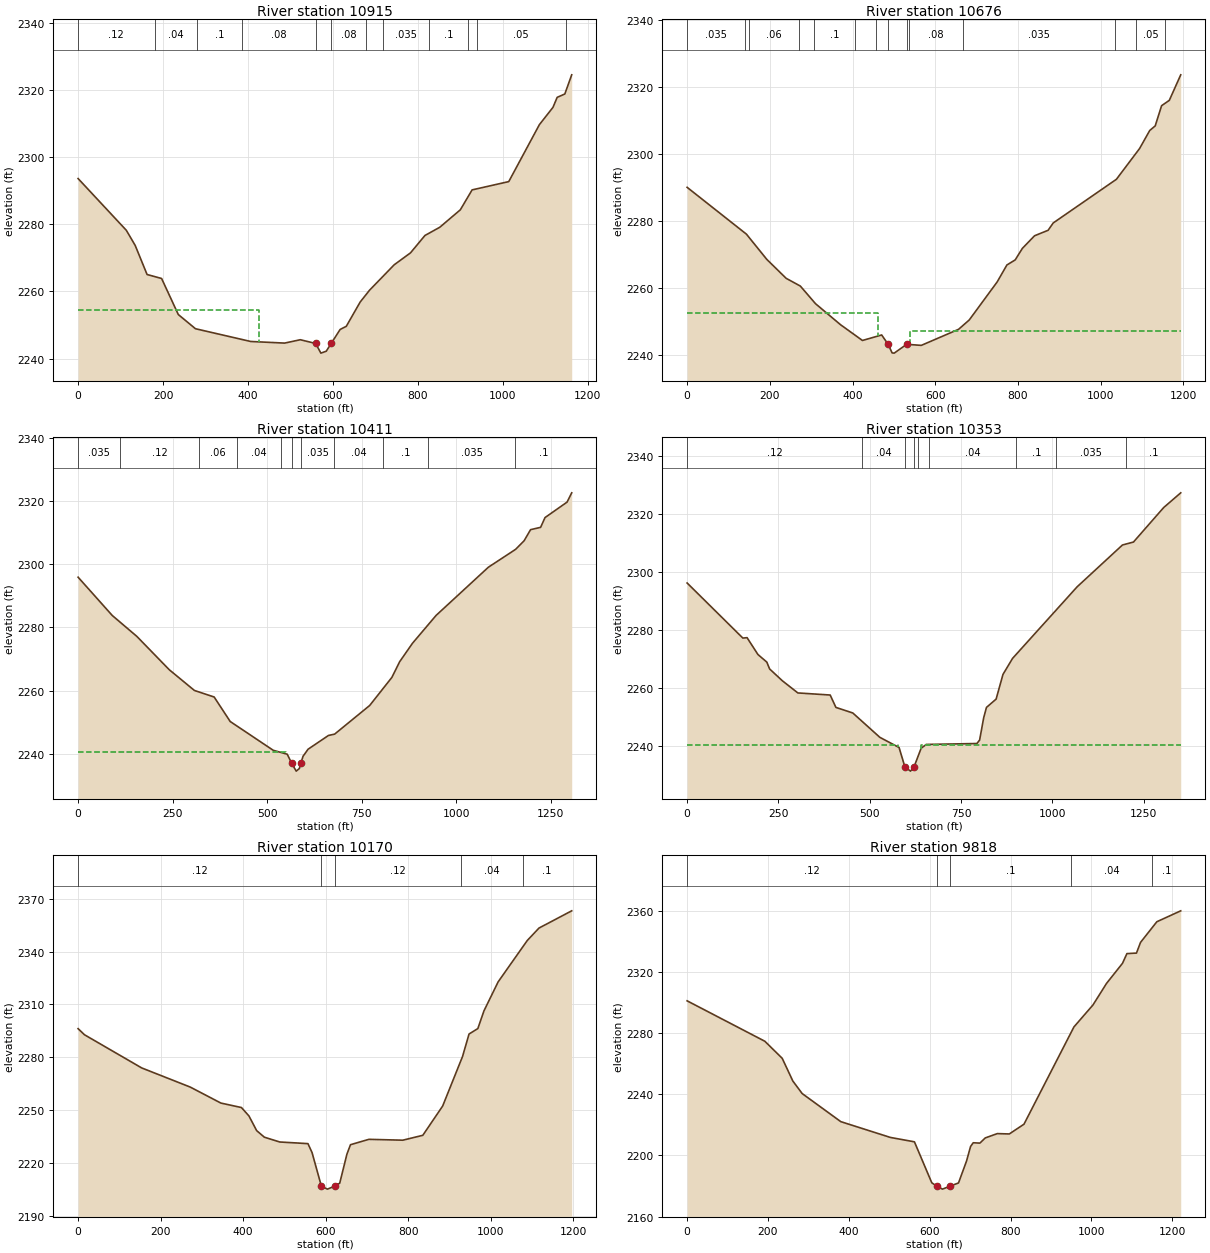
Type RM Length L Ch R = 1 ,10915   ,242.8,238.3,222
XS GIS Cut Line= 4
1974762.17231036237798.9500366571974446.19042476237915.980364654
1973957.00365374238147.7004140891973692.51511246238250.687102726
#Sta/Elev= 30
       0 2293.65   113.5 2278.24   134.5 2273.71   162.4 2265.06   196.6 2263.88
   235.9 2253.14   276.3 2248.91   406.4 2245.11   486.2 2244.63   523.1 2245.63
   559.3 2244.52   571.6 2241.64   584.2 2242.21   596.2 2244.59   616.9 2248.69
   631.4 2249.63   664.1 2256.86   685.9 2260.35   744.2 2267.96   782.5  2271.5
   816.6 2276.69   851.5 2279.14   899.9 2284.34   927.6 2290.27  1013.9 2292.74
    1086  2309.7    1118 2314.86  1127.9 2317.84  1145.9 2318.84  1162.1 2324.55
#Mann= 12 ,-1 , 0
       0     .12       0     180     .04       0     280      .1       0
  386.96     .08       0   559.3    .045       0   596.2     .08       0
  676.96      .1       0  716.96    .035       0  826.96      .1       0
  918.25    .035       0  938.25     .05       0 1148.25      .1       0
#XS Ineff= 2 , 0
          426.36 2254.35
Permanent Ineff=
       F       F
Bank Sta=559.3,596.2
XS Rating Curve= 0 ,0
Exp/Cntr(USF)=0,0
Exp/Cntr=0.3,0.1

Type RM Length L Ch R = 1 ,10676   ,266.2,265.5,263.7
XS GIS Cut Line= 4
1974619.86343151237489.7559100881974396.56956569237651.959944692
1974055.30912925237944.7698253411973680.34395835238224.940430567
#Sta/Elev= 30
       0 2290.02   143.5 2276.06   192.7 2268.55   239.5 2262.91   273.8  2260.6
   310.5 2255.35   371.1 2249.08     424 2244.39   470.5 2246.03  486.322243.204
   495.7 2240.69   500.8 2240.62     531 2243.25   566.3 2242.93   656.4 2247.71
   682.2 2250.49   749.9 2261.85   773.3 2266.88   793.4  2268.4   810.8 2271.84
   840.2 2275.59     873 2277.22   885.3  2279.4  1038.2 2292.42  1094.2 2301.58
  1118.7 2306.95    1132 2308.33  1147.4 2314.34  1166.1 2315.94  1193.7 2323.54
#Mann= 14 ,-1 , 0
       0    .035       0     140      .1       0     150     .06       0
     270     .04       0  305.99      .1       0  405.99    .035       0
  455.99      .1       0  486.32    .045       0     531      .1       0
  535.99     .08       0  665.99    .035       0 1035.65      .1       0
 1085.65     .05       0 1155.65      .1       0
#XS Ineff= 2 , 0
          462.46 2252.58  538.77         2247.19
Permanent Ineff=
       F       F
Bank Sta=486.32,531
XS Rating Curve= 0 ,0
Exp/Cntr(USF)=0,0
Exp/Cntr=0.5,0.3

Type RM Length L Ch R = 1 ,10411   ,56.3,57.7,59.2
XS GIS Cut Line= 4
1974596.69142657237367.5762476591974147.99714903237531.886828167
1973943.66219634237734.115234946 1973652.9588616  238189.1291502
#Sta/Elev= 30
       0 2295.87    90.2 2283.77   155.4 2277.13     241 2266.59   307.6 2260.02
   359.8 2257.95   402.2  2250.2   516.1 2241.08   553.1 2239.84   564.42237.061
   576.8 2234.49   585.1 2235.31  589.172237.057   594.8 2239.18   608.1 2241.42
   662.1 2245.78   678.4  2246.2   771.1 2255.27   829.8 2264.16   850.3 2269.11
   884.3 2274.96   946.6 2283.76  1084.9 2299.02  1156.9 2304.68  1179.4 2307.39
  1196.5 2310.91  1223.1 2311.65  1234.7 2314.73  1293.1 2319.64  1305.3 2322.57
#Mann= 11 ,-1 , 0
       0    .035       0     110     .12       0     320     .06       0
     420     .04       0  537.83    .035       0   564.4    .045       0
  589.17    .035       0  677.83     .04       0  805.32      .1       0
  925.32    .035       0 1155.32      .1       0
#XS Ineff= 2 , 0
          549.63 2240.48     603         2240.48
Permanent Ineff=
       F       F
Bank Sta=564.4,589.17
XS Rating Curve= 0 ,0
Exp/Cntr(USF)=0,0
Exp/Cntr=0.5,0.3

Type RM Length L Ch R = 1 ,10353   ,173.8,182.9,186.4
XS GIS Cut Line= 4
1974552.45396259237218.0114884791974124.82514408237483.436272377
1973909.95746188237675.1319496361973636.10649437238163.850599352
#Sta/Elev= 30
       0 2296.12   152.6 2277.13   164.1 2277.27   193.9 2271.46   218.2 2268.84
   225.9 2266.48   260.7 2262.41   303.2 2258.21   391.7 2257.49   407.4 2253.22
   453.6  2251.3   527.8 2242.89   580.3  2239.4  596.29 2232.69   611.6 2231.25
  621.252232.692   640.7 2239.13   654.7 2240.45   793.3 2240.77   800.8 2241.94
   812.1 2249.71   819.6 2253.22     846 2256.08   864.8  2264.6   891.1 2270.13
  1067.9 2294.81  1191.9 2309.22  1222.1 2310.24  1304.8 2322.13  1351.5 2327.21
#Mann= 9 ,-1 , 0
       0     .12       0     480     .04       0  596.29    .045       0
  621.25     .04       0  633.31    .035       0  663.31     .04       0
  901.26      .1       0 1011.26    .035       0 1201.26      .1       0
#XS Ineff= 2 , 0
             578 2240.11     640         2240.11
Permanent Ineff=
       F       F
Bank Sta=596.29,621.25
XS Rating Curve= 0 ,0
Exp/Cntr(USF)=0,0
Exp/Cntr=0.5,0.3

Type RM Length L Ch R = 1 ,10170   ,340,352.3,359.9
XS GIS Cut Line= 4
1974476.61831004237169.5609326881974105.86623095237323.338783676
1973722.47487643237529.7802822631973404.38644493237696.197408675
#Sta/Elev= 30
       0 2296.25    15.6 2292.77   154.1 2273.93   271.6 2263.06   345.9 2253.96
   395.7 2251.42   413.9 2246.64   432.6 2238.29   451.3 2234.56   488.5 2231.84
   556.8 2230.91   566.8 2225.82  589.322206.774     604 2205.05  621.932206.774
   633.8 2208.43   651.2 2224.89   659.9  2230.3   704.5 2233.35   786.6 2232.86
   835.1 2235.64   883.2 2252.28   931.3 2280.41   947.1  2293.2   968.4  2296.3
   983.2 2306.35  1017.6 2322.85  1088.1 2346.34  1116.5 2353.42  1195.8 2363.22
#Mann= 5 ,-1 , 0
       0     .12       0  589.32    .045       0  621.93     .12       0
  926.82     .04       0 1076.82      .1       0
Bank Sta=589.32,621.93
XS Rating Curve= 0 ,0
Exp/Cntr(USF)=0,0
Exp/Cntr=0.3,0.1

Type RM Length L Ch R = 1 ,9818    ,389.3,396.6,393.1
XS GIS Cut Line= 4
 1974453.4463051237017.8896276041974156.42333264237047.381270259
1973579.22975496237116.8972850891973246.39550214237190.626391728
#Sta/Elev= 30
       0 2301.31   192.3 2274.81   235.2 2263.64   261.5 2248.75   284.6 2240.55
   380.1 2222.15   502.7 2211.81   562.2 2208.93   605.1 2182.09  617.432179.922
   631.6 2177.94  650.492179.922   671.2 2181.99   691.1 2196.37     701 2205.87
   707.6 2208.32   724.1 2208.09   737.3 2211.48   767.1 2214.31   796.8 2214.09
   833.1 2220.47   956.7 2284.22  1003.7 2298.58  1037.3 2312.73  1076.7 2325.86
  1087.7 2332.25  1111.3 2332.59  1121.4 2339.61  1161.7 2353.12  1220.8 2360.28
#Mann= 5 ,-1 , 0
       0     .12       0  617.43    .045       0  650.49      .1       0
  949.85     .04       0 1149.85      .1       0
Bank Sta=617.43,650.49
XS Rating Curve= 0 ,0
Exp/Cntr(USF)=0,0
Exp/Cntr=0.3,0.1

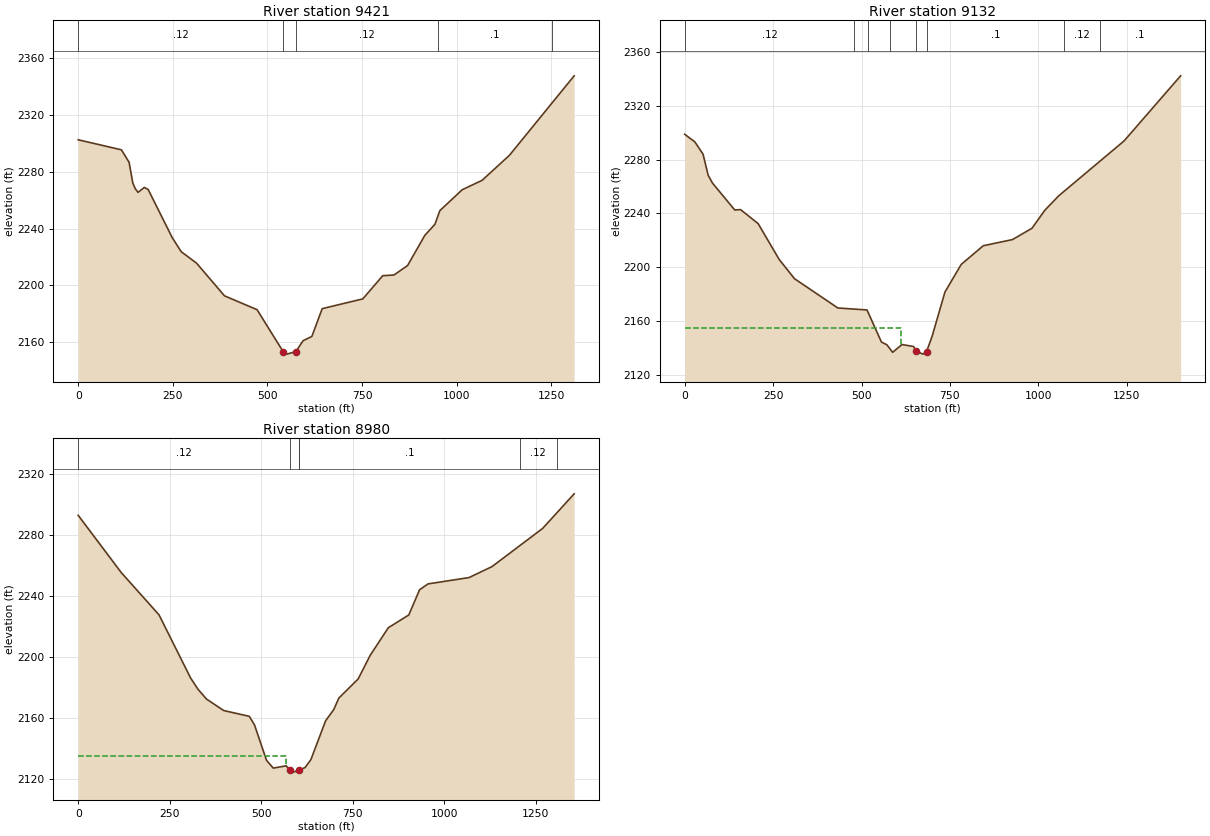
Type RM Length L Ch R = 1 ,9421    ,283.3,289,282.1
XS GIS Cut Line= 4
  1974455.552851236824.0874044411974053.20258335236733.505930571
 1973705.6225092236708.2273797231973155.81402827236710.333925627
#Sta/Elev= 30
       0 2302.64   114.2 2295.57   134.4 2286.83   144.5 2271.96     151  2268.1
     158 2265.61   174.8 2269.08   184.9 2267.61   248.8 2233.57   272.3 2223.78
   312.7 2215.76   386.6 2192.71   472.7 2182.96  541.492153.467   551.7 2151.65
  575.282153.465   594.4 2161.14   617.5  2164.1   644.8 2183.68   752.1 2190.56
   804.9  2206.9   834.4 2207.38   870.5 2214.04   916.1 2235.33   942.7 2243.09
   955.8 2252.73  1014.9 2267.46  1067.3 2274.06  1139.5 2291.66  1310.7 2347.69
#Mann= 5 ,-1 , 0
       0     .12       0  541.49    .045       0  575.28     .12       0
  950.92      .1       0 1250.92     .04       0
Bank Sta=541.49,575.28
XS Rating Curve= 0 ,0
Exp/Cntr(USF)=0,0
Exp/Cntr=0.3,0.1

Type RM Length L Ch R = 1 ,9132    ,141.9,152.2,157.1
XS GIS Cut Line= 4
1974480.83140185236556.5560746391973996.32584394236487.040059809
1973572.91011725236465.9746007691973084.19146753236468.081146673
#Sta/Elev= 30
       0 2298.81    28.8 2293.13      52    2284    66.4 2268.39    78.5  2262.6
   141.5 2242.61     158 2242.86   207.7 2232.47   267.2 2205.86   310.5 2191.58
   433.1 2169.84   515.5 2168.38   556.2 2144.59   571.6 2142.53     588 2136.95
   614.3 2142.72   647.1 2141.24  654.542137.823   673.4 2135.59  683.982137.523
   699.7 2148.98   735.8 2181.66   781.8 2202.18   844.2 2216.05   926.6  2220.6
   982.1 2229.06  1018.3 2242.44  1057.6 2253.12  1242.4 2293.89  1402.1 2342.17
#Mann= 8 ,-1 , 0
       0     .12       0     480      .1       0  519.47     .12       0
  579.47      .1       0  654.54    .045       0  683.98      .1       0
 1073.41     .12       0 1173.41      .1       0
#XS Ineff= 2 , 0
          612.03 2154.64
Permanent Ineff=
       F       F
Bank Sta=654.54,683.98
XS Rating Curve= 0 ,0
Exp/Cntr(USF)=0,0
Exp/Cntr=0.3,0.1

Type RM Length L Ch R = 1 ,8980    ,147.7,141.6,127.3
XS GIS Cut Line= 4
1974489.08309402236514.8840910551974023.65041168236429.104688848
1973813.96742851236324.263197261 1973169.0334045236384.626480296
#Sta/Elev= 30
       0 2292.79   117.4 2255.39   220.8 2227.68     307  2186.4   327.6 2178.89
   350.9 2172.49   397.6 2165.03   467.6 2161.24   481.8 2155.65   514.8  2132.4
   533.2 2127.36   568.6 2128.84   578.4 2125.92   588.2 2124.72   602.8 2125.93
     620 2127.72   635.9 2132.86   676.2 2158.33   698.3 2165.61   712.4  2173.2
   765.1 2185.69     798 2201.13   847.5 2219.21   903.5 2227.55   933.1  2244.1
   956.2  2247.9  1068.3 2252.05  1130.9 2259.21  1269.3  2284.2  1355.5 2306.85
#Mann= 6 ,-1 , 0
       0     .12       0   578.4    .045       0   602.8     .12       0
  603.27      .1       0  1207.7     .12       0  1307.7      .1       0
#XS Ineff= 2 , 0
          566.64 2135.56
Permanent Ineff=
       F       F
Bank Sta=578.4,602.8
XS Rating Curve= 0 ,0
Exp/Cntr(USF)=0,0
Exp/Cntr=0.3,0.1