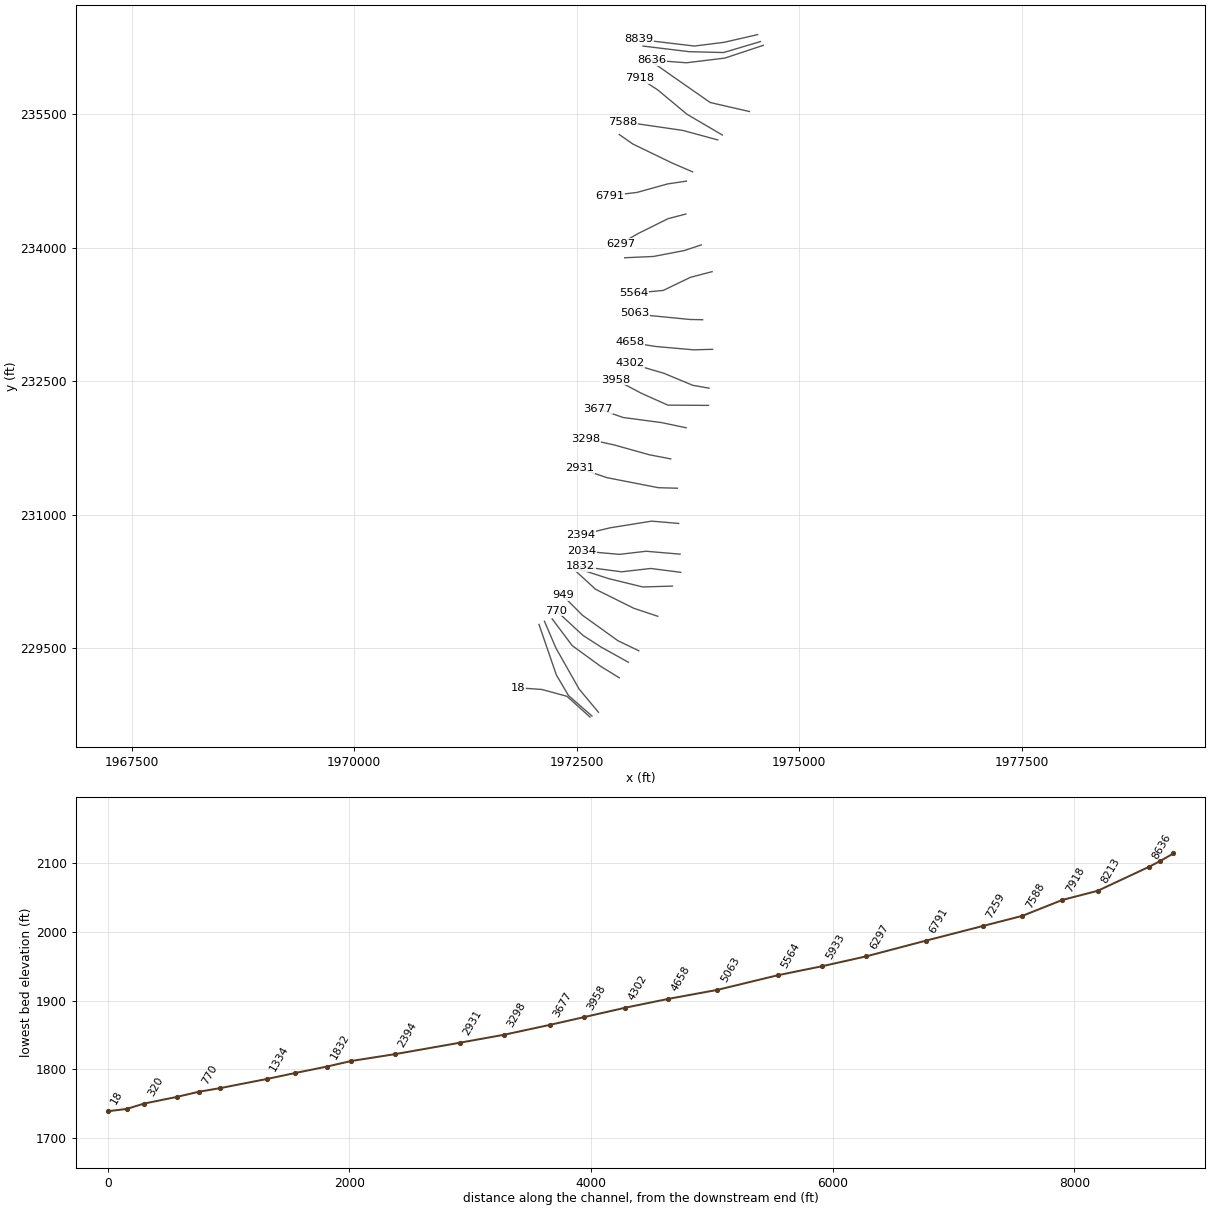
HEC-RAS study JUMPNGBR.prj: JUMPNGBR

--- JUMPNGBR.g01 (geometry) --- (continued)

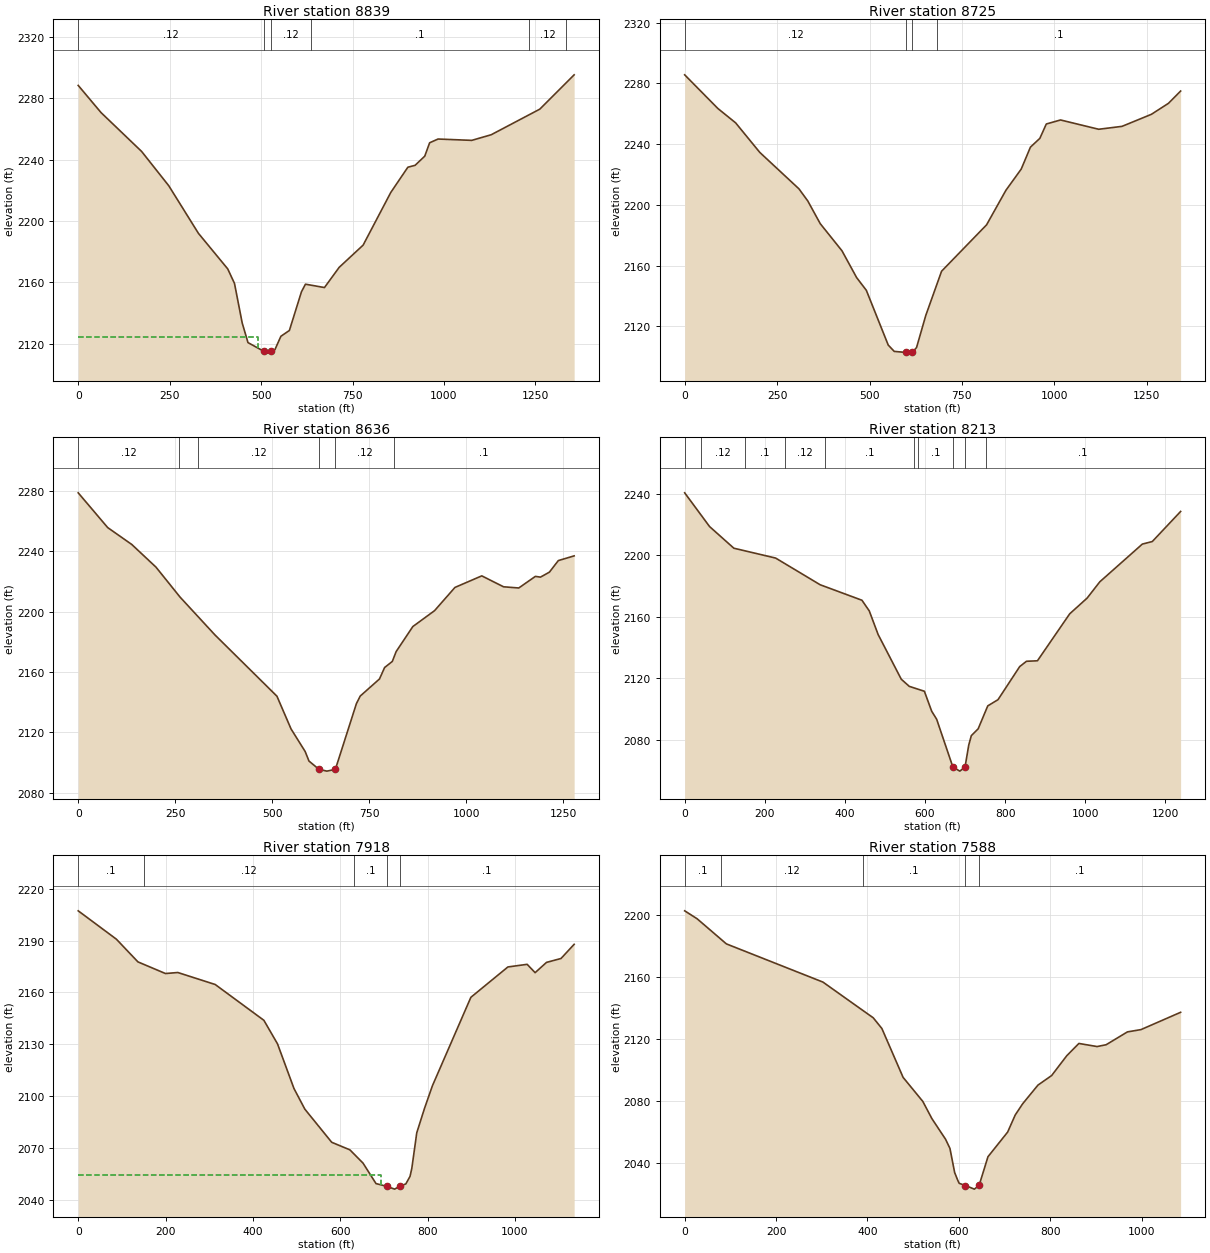
Type RM Length L Ch R = 1 ,8839    ,106.2,113.1,101.5
XS GIS Cut Line= 4
1974532.86304391 236392.756975421974156.24186022236306.074322031
1973821.46747471236264.2275238421973193.76550189236338.953949178
#Sta/Elev= 30
       0 2288.36    62.4 2270.64   173.5 2245.26   247.6 2222.93   328.7 2191.89
   408.8 2168.71   427.3 2159.24   448.4 2133.41   464.2 2120.64     508 2114.89
   514.6 2113.77   527.8 2114.96   537.7 2115.98   554.2 2124.76   577.4 2128.55
   610.4 2153.76   621.3 2158.73   673.3 2156.54   713.6 2169.73     779  2184.2
   854.6 2218.53   901.3    2235   921.1 2236.25   947.5 2242.21   960.9 2250.95
   983.9 2253.39  1076.1 2252.52  1129.3 2256.19  1262.1 2272.88    1356 2295.26
#Mann= 6 ,-1 , 0
       0     .12       0     508    .045       0   527.8     .12       0
  636.47      .1       0 1233.85     .12       0 1333.85      .1       0
#XS Ineff= 2 , 0
          491.16 2124.34
Permanent Ineff=
       F       F
Bank Sta=508,527.8
XS Rating Curve= 0 ,0
Exp/Cntr(USF)=0,0
Exp/Cntr=0.3,0.1

Type RM Length L Ch R = 1 ,8725    ,87.1,89.8,95.7
XS GIS Cut Line= 4
 1974564.8382661236314.6786454621974150.82397917236191.200700237
1973763.44219023 236200.885244961973245.31904752236263.834785663
#Sta/Elev= 30
       0 2285.59    89.8 2263.42   137.9 2253.95   203.2  2234.5   309.1 2210.51
   333.1 2202.49   366.7 2187.58   425.5 2169.71   465.2 2152.04   491.4 2143.67
   550.6 2107.64   566.9 2103.45   599.7 2102.76     603 2102.32   616.1  2102.9
   627.2    2106   652.2 2127.16   694.9 2156.26   816.6  2186.8   868.9 2209.54
   910.3  2223.5   935.3 2237.98   960.7 2243.75   978.2 2253.21  1016.7 2255.86
  1119.9 2249.74  1183.1 2251.66  1262.5 2259.59  1308.5  2266.8  1341.5  2274.9
#Mann= 4 ,-1 , 0
       0     .12       0   599.7    .045       0   616.1     .12       0
  682.04      .1       0
Bank Sta=599.7,616.1
XS Rating Curve= 0 ,0
Exp/Cntr(USF)=0,0
Exp/Cntr=0.3,0.1

Type RM Length L Ch R = 1 ,8636    ,438.7,422.5,395.3
XS GIS Cut Line= 4
1974596.69142657236272.1723776061974164.84951626236128.927256137
1973733.00760595236076.2636085391973345.40315962236105.755251194
#Sta/Elev= 30
       0  2278.7      76 2255.67   138.2 2244.45   200.5 2229.45   262.7 2209.56
   352.5 2184.53   512.4  2143.9   548.7 2122.23   585.1 2107.27     595 2100.91
  620.912095.417   641.3 2094.24  663.062095.417   717.3    2139   727.2 2144.01
   776.8 2155.33     790 2162.91   809.8 2166.92   819.8 2173.51   862.7 2190.05
   918.8  2200.6   971.4    2216  1040.5 2223.66  1096.8 2216.41  1135.9 2215.63
  1178.7 2223.31  1191.9 2222.83  1214.9 2226.12  1237.9 2233.79  1278.7 2236.91
#Mann= 6 ,-1 , 0
       0     .12       0     260      .1       0     310     .12       0
  620.91    .045       0  663.06     .12       0  814.98      .1       0
Bank Sta=620.91,663.06
XS Rating Curve= 0 ,0
Exp/Cntr(USF)=0,0
Exp/Cntr=0.3,0.1

Type RM Length L Ch R = 1 ,8213    ,294.6,294.8,290.6
XS GIS Cut Line= 4
1974440.80702968235528.5616735121974000.53893575235629.675876901
1973583.44284677235920.3792116461973355.93588914236080.476700346
#Sta/Elev= 30
       0 2240.62    62.2 2218.66   122.8 2204.58   227.1 2198.17   338.2 2180.81
   442.6 2170.72   460.9 2163.79     483 2148.44   540.8 2119.33   560.8 2114.69
   598.5  2111.5   616.8 2098.49   629.2 2093.27   669.72062.171     687 2059.53
  699.992062.176   709.3  2076.5   715.7 2082.61   732.8 2087.06   756.8    2102
   782.3 2106.01   836.5 2127.54   853.4 2131.01   880.8 2131.33   961.4  2161.9
  1004.9 2172.13  1036.5 2182.71  1142.7 2207.26  1167.6 2208.93  1238.3 2228.49
#Mann= 10 ,-1 , 0
       0      .1       0      40     .12       0     150      .1       0
     250     .12       0     350      .1       0  571.73     .12       0
  581.73      .1       0   669.7    .045       0  699.99     .12       0
  751.73      .1       0
Bank Sta=669.7,699.99
XS Rating Curve= 0 ,0
Exp/Cntr(USF)=0,0
Exp/Cntr=0.3,0.1

Type RM Length L Ch R = 1 ,7918    ,315.1,330.6,341.4
XS GIS Cut Line= 4
1974137.28237233235264.2291726761973738.51236582 235498.28982867
1973409.09366479235772.8054128611973203.92938608235905.728748364
#Sta/Elev= 30
       0 2207.24    87.4 2190.82   136.8 2177.67   199.8 2170.93   228.1 2171.52
   313.7 2164.58   425.2 2143.84   456.4 2130.21   494.1 2104.35     519  2092.4
   580.5 2073.21   622.2 2068.83   652.3 2061.13     682 2049.29  706.292047.728
   724.7 2046.09  735.992047.729   750.3 2049.12   759.9 2053.48     764  2058.2
   775.3 2078.73     793 2092.84   811.1 2105.92   899.2 2157.16     984 2174.74
  1028.1 2176.26  1046.3 2171.43  1072.4 2177.38  1105.6 2179.64  1135.7 2187.85
#Mann= 5 ,-1 , 0
       0      .1       0     150     .12       0  632.39      .1       0
  706.29    .045       0  735.99      .1       0
#XS Ineff= 2 , 0
          693.25 2054.26
Permanent Ineff=
       F       F
Bank Sta=706.29,735.99
XS Rating Curve= 0 ,0
Exp/Cntr(USF)=0,0
Exp/Cntr=0.3,0.1

Type RM Length L Ch R = 1 ,7588    ,336.7,329,321.6
XS GIS Cut Line= 4
1974085.26889322 235209.615019611973692.56712594235316.242651785
1973229.64716186235383.8601746281973021.59324543235415.068262094
#Sta/Elev= 30
       0 2202.51    27.1 2197.42    91.3 2181.18   302.5 2156.55   412.6  2133.5
   431.5  2126.6   477.9 2095.09     521 2079.59   540.9 2068.49   570.8 2055.18
   580.4 2049.28   590.7  2033.7   597.3 2028.84   600.6 2026.75  614.242025.348
   633.8 2023.01  644.16 2025.35   663.6 2043.91   706.7 2059.83   723.3 2070.88
   739.5 2078.06     773 2090.11   802.9 2096.27     836 2109.05   862.5 2116.97
   902.3 2114.97   922.2 2116.15   968.7 2124.42   998.5 2125.91  1085.1 2137.06
#Mann= 5 ,-1 , 0
       0      .1       0      80     .12       0     390      .1       0
  614.24    .045       0  644.16      .1       0
Bank Sta=614.24,644.16
XS Rating Curve= 0 ,0
Exp/Cntr(USF)=0,0
Exp/Cntr=0.3,0.1

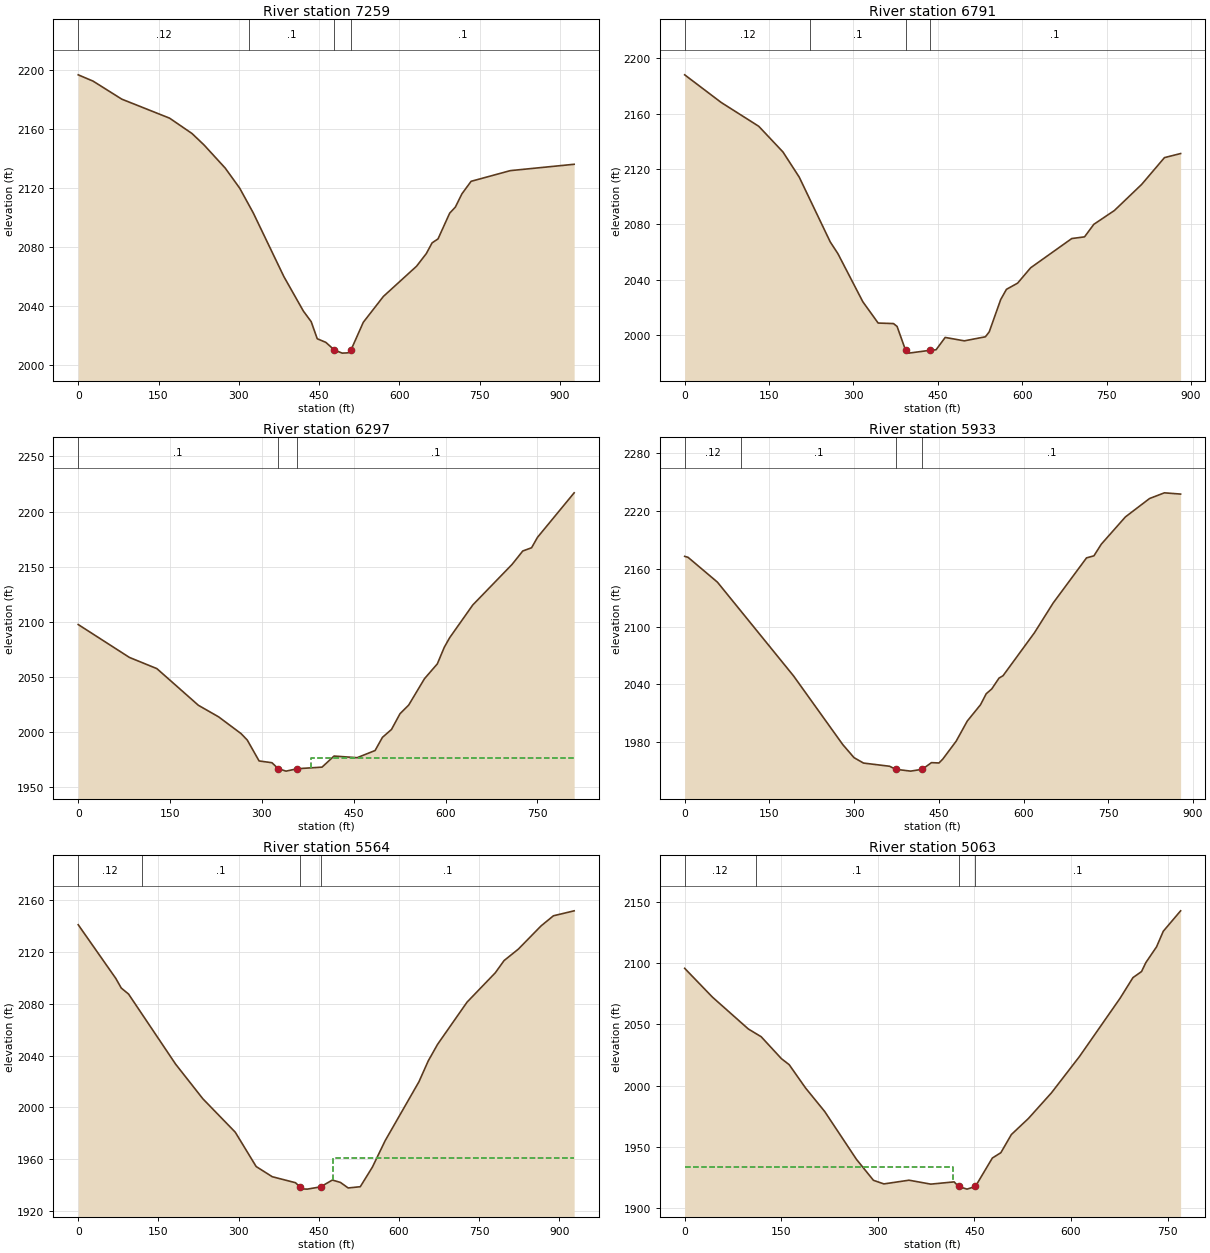
Type RM Length L Ch R = 1 ,7259    ,446.3,467.6,486.4
XS GIS Cut Line= 4
1973802.08439585234851.0109775251973573.80301531234949.258660288
1973131.68844287235163.0918521841972978.53764327235270.008448132
#Sta/Elev= 30
       0 2197.06    27.8 2192.78    81.4 2180.55   170.7 2167.65   212.6 2157.23
   235.1 2149.45   274.6 2133.77   301.6 2120.17   326.9 2103.42   384.2 2060.12
   420.6 2036.74   435.2 2029.55   446.5 2017.96   462.5 2015.52   478.72010.255
   493.2  2008.2   504.4 2008.41  509.462010.255   532.5 2029.11     570 2046.65
     632 2067.17   650.2 2075.73   661.1 2083.05   672.1 2085.71   693.9 2103.18
   704.5 2107.29   716.7 2116.27   733.9 2124.79   807.2 2132.05   926.4 2136.36
#Mann= 4 ,-1 , 0
       0     .12       0  318.53      .1       0   478.7    .045       0
  509.46      .1       0
Bank Sta=478.7,509.46
XS Rating Curve= 0 ,0
Exp/Cntr(USF)=0,0
Exp/Cntr=0.3,0.1

Type RM Length L Ch R = 1 ,6791    ,490.2,494.5,495.3
XS GIS Cut Line= 4
1973732.73309037234746.984019305 1973521.7895362234715.198004294
1973177.92264653234619.839959259 1972868.7314096234582.274668791
#Sta/Elev= 30
       0  2188.1    64.9 2168.14   131.7 2150.92   174.7 2132.38   203.6 2114.23
   258.8 2067.38   272.4 2058.91   316.7 2024.18   343.9  2008.8   371.2 2008.42
   377.6 2006.33  392.77 1989.08   398.4 1987.07  435.461989.077   446.9 1989.49
   463.1 1998.41   497.1 1995.94   534.6 1998.87   541.4 2002.44   561.8  2025.8
     572 2033.15   591.8 2037.61     615 2048.71   688.1 2069.84   710.8 2071.05
   727.3  2080.1   763.9  2090.1   812.3 2108.92   852.9  2128.3   881.6 2131.24
#Mann= 4 ,-1 , 0
       0     .12       0  223.32      .1       0  392.77    .045       0
  435.46      .1       0
Bank Sta=392.77,435.46
XS Rating Curve= 0 ,0
Exp/Cntr(USF)=0,0
Exp/Cntr=0.3,0.1

Type RM Length L Ch R = 1 ,6297    ,370.6,364,356.8
XS GIS Cut Line= 4
1973726.95381491 234377.110390081973527.56881166 234325.09691097
 1973195.2604729234160.3875604551972992.98583191234044.802051322
#Sta/Elev= 30
       0 2097.37    83.6 2067.51   128.5 2057.32   196.3 2024.02   229.3 2013.53
     266  1998.3   276.1 1992.45   295.4 1973.49   316.4 1971.88  326.691966.435
   339.4 1964.25  357.951966.437   398.2 1967.89   417.8 1977.94   455.5 1976.45
   484.8 1982.95   496.8 1994.91   511.6 2002.08   525.5 2016.36   539.7 2024.24
   565.4 2048.11   586.5 2061.69   597.8  2076.7   606.5 2085.32   644.3  2115.1
   708.6 2152.02     726 2164.16   740.4 2167.09   750.1 2176.61   809.9 2216.97
#Mann= 3 ,-1 , 0
       0      .1       0  326.69    .045       0  357.95      .1       0
#XS Ineff= 2 , 0
                          379.68         1976.04
Permanent Ineff=
       F       F
Bank Sta=326.69,357.95
XS Rating Curve= 0 ,0
Exp/Cntr(USF)=0,0
Exp/Cntr=0.3,0.1

Type RM Length L Ch R = 1 ,5933    ,361.5,368.5,376.7
XS GIS Cut Line= 4
1973900.33207861234030.3538626811973709.61598854233966.781832657
1973362.85946114233900.3201649061973039.22003557233885.871976264
#Sta/Elev= 30
       0  2173.1       6 2172.07    57.9 2146.36   192.8 2048.86   279.9 1977.54
   299.9 1963.93   316.6 1958.33   362.9    1955  373.411951.887   400.2 1949.95
  420.731951.887   436.9 1958.76   450.3 1958.43     457 1962.45   480.7 1981.08
   500.4 2002.02   523.8 2018.91   533.9 2030.35   543.8 2035.42   556.6 2046.65
   563.7 2049.09   619.3 2093.74   652.4 2124.61   711.5 2171.52   724.6 2173.65
   737.7 2185.79   780.4 2214.11   823.1  2233.2   849.4 2239.11   878.1  2237.8
#Mann= 4 ,-1 , 0
       0     .12       0     100      .1       0  373.41    .045       0
  420.73      .1       0
Bank Sta=373.41,420.73
XS Rating Curve= 0 ,0
Exp/Cntr(USF)=0,0
Exp/Cntr=0.3,0.1

Type RM Length L Ch R = 1 ,5564    ,507,500.7,468.3
XS GIS Cut Line= 4
 1974021.6968632233729.8315389351973778.96729402233666.259508912
1973472.66569482233518.8879847671973137.46771833233487.101969756
#Sta/Elev= 30
       0 2141.08    70.3  2099.6    80.5 2092.17    94.1 2087.55   182.2 2033.34
   233.1  2006.6   293.7 1980.78   332.8 1954.24   362.9 1946.37   406.4 1941.73
  413.921938.749   417.5 1936.98   428.4 1936.78   453.2 1938.52   475.3 1943.79
   490.3 1941.98   504.9 1937.68   527.5 1938.64   550.2 1953.81     574 1974.18
   637.3  2019.8   654.7 2035.93   672.1 2048.68   727.2 2081.26     780 2103.93
   796.4 2113.38     823 2122.19   865.6 2140.17   888.7 2147.99   927.5 2151.83
#Mann= 4 ,-1 , 0
       0     .12       0     120      .1       0  413.92    .045       0
   453.2      .1       0
#XS Ineff= 2 , 0
                          475.64         1960.93
Permanent Ineff=
       F       F
Bank Sta=413.92,453.2
XS Rating Curve= 0 ,0
Exp/Cntr(USF)=0,0
Exp/Cntr=0.3,0.1

Type RM Length L Ch R = 1 ,5063    ,415.1,405.6,402.1
XS GIS Cut Line= 4
1973914.78026725233189.4692837381973773.18801856233192.358921466
1973331.07344613233235.7034873911973149.02626924233264.599864674
#Sta/Elev= 30
       0 2095.85    43.1 2072.34    98.9 2046.29   118.8 2039.98   150.3 2022.03
   162.3 2017.15   187.7 1998.12   217.4 1978.93   266.8  1939.8   293.2 1922.67
   309.4 1919.74   348.4 1922.77   382.2 1919.56   418.5  1921.4  425.271917.693
   438.5 1915.48  451.561917.691   477.8 1940.88     491 1945.23   507.4  1960.1
   533.9 1973.22   569.6 1994.15   613.2 2023.87   676.3  2071.5   696.2 2088.28
   709.5 2093.22   716.2 2100.54   732.8 2113.39   743.3 2126.17   770.2 2142.83
#Mann= 4 ,-1 , 0
       0     .12       0     110      .1       0  425.27    .045       0
  451.56      .1       0
#XS Ineff= 2 , 0
          417.19 1933.66
Permanent Ineff=
       F       F
Bank Sta=425.27,451.56
XS Rating Curve= 0 ,0
Exp/Cntr(USF)=0,0
Exp/Cntr=0.3,0.1

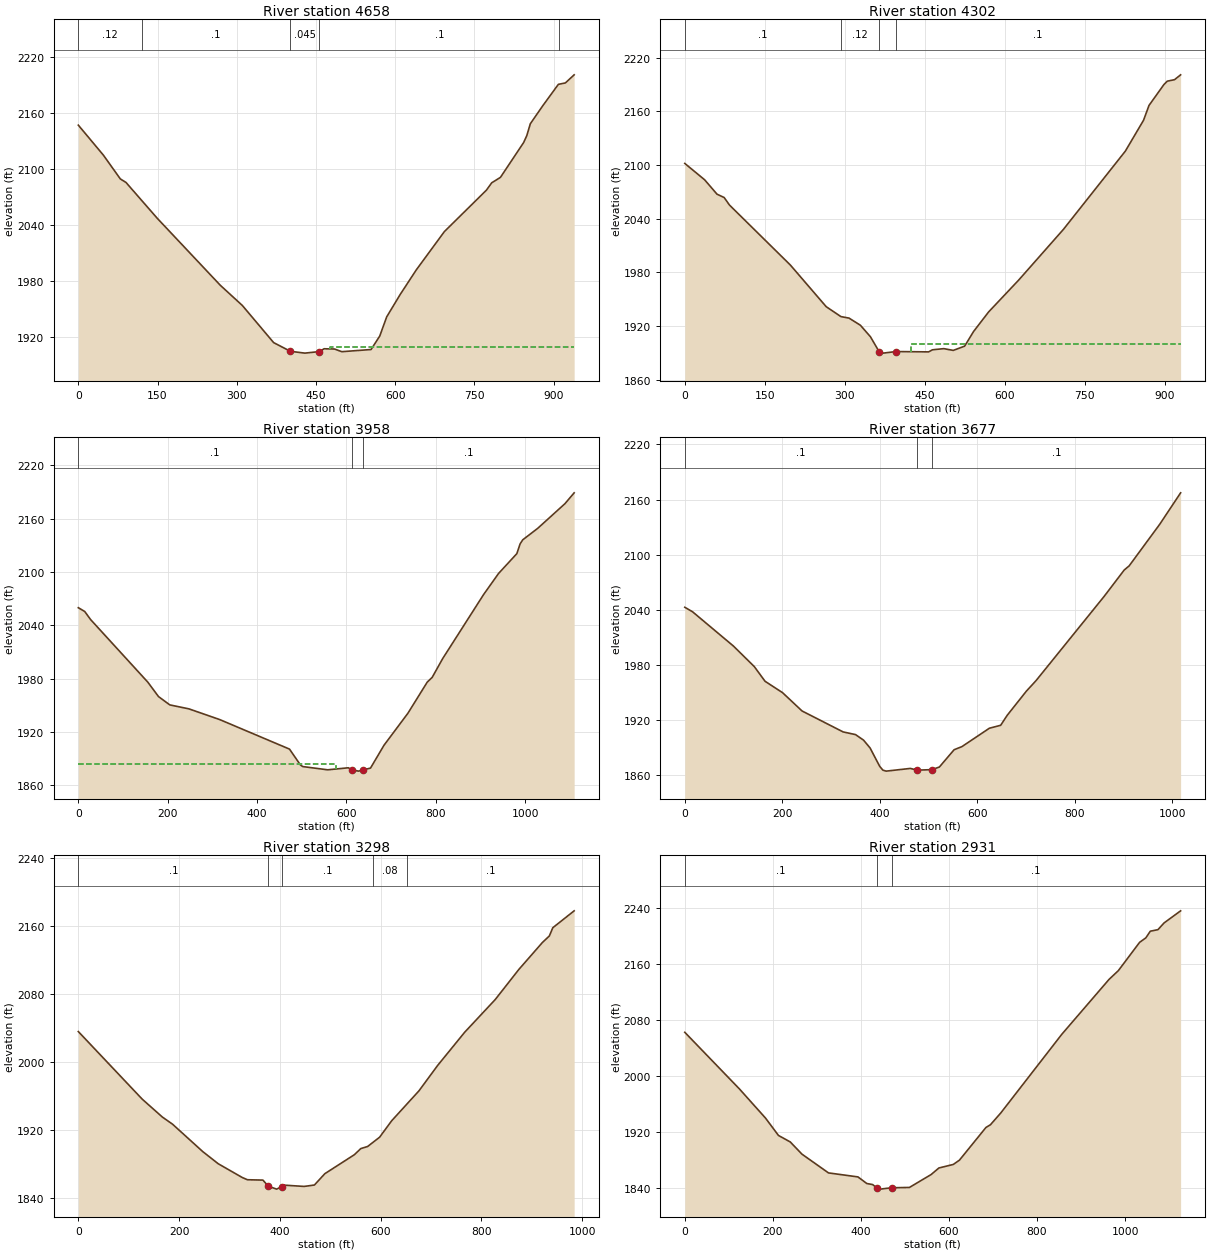
Type RM Length L Ch R = 1 ,4658    ,354.4,355.3,344.3
XS GIS Cut Line= 4
1974027.47613866232857.1609449811973813.64294676232851.381669524
 1973388.8662007232888.9469599921973094.12315241232935.181163645
#Sta/Elev= 30
       0 2146.77    47.6 2114.51    79.5 2089.14    90.2 2085.38   149.3 2047.02
   268.8 1975.14   310.5  1953.5   369.8 1913.68  401.471904.389   428.8 1902.43
   456.4  1904.1   465.3  1907.1     485 1906.84   498.8 1903.98   554.2 1906.29
   570.7  1920.8   583.8  1941.3   609.5 1965.43   639.8 1991.62     693 2032.69
   772.7 2077.16   782.6 2084.96   799.2 2090.84   843.1 2128.16   849.1 2135.67
   855.7 2148.23   878.9 2167.25   908.8 2190.48   922.1 2192.02   938.7  2200.7
#Mann= 5 ,-1 , 0
       0     .12       0     120      .1       0  401.47    .045       0
   456.4      .1       0  910.35     .12       0
#XS Ineff= 2 , 0
                          475.74         1909.09
Permanent Ineff=
       F       F
Bank Sta=401.47,456.4
XS Rating Curve= 0 ,0
Exp/Cntr(USF)=0,0
Exp/Cntr=0.3,0.1

Type RM Length L Ch R = 1 ,4302    ,344.2,344.7,340.5
XS GIS Cut Line= 4
1973987.02121046232420.8256480041973804.97403357232452.611663015
1973478.44497027232588.4246362461973102.79206559232698.230869923
#Sta/Elev= 30
       0  2101.8    37.2 2083.48    60.5 2067.36    73.8 2063.67    83.8 2055.24
   197.9 1988.19   265.2 1941.56   292.8 1930.48     308  1928.8   329.3 1920.81
   348.1 1907.97  364.231891.439     372 1889.63   395.7 1891.38   457.3 1891.03
   464.4 1893.34   485.7 1894.64   503.4 1892.68   524.8 1897.44   541.4 1913.71
   569.7 1935.67   626.1 1971.31   709.9 2027.95   826.1 2115.52   860.3 2150.11
   870.5 2166.67   898.5 2190.04   904.7 2193.77   918.4 2195.47   929.8 2200.89
#Mann= 4 ,-1 , 0
       0      .1       0   292.8     .12       0  364.23    .045       0
   395.7      .1       0
#XS Ineff= 2 , 0
                             425         1900.36
Permanent Ineff=
       F       F
Bank Sta=364.23,395.7
XS Rating Curve= 0 ,0
Exp/Cntr(USF)=0,0
Exp/Cntr=0.3,0.1

Type RM Length L Ch R = 1 ,3958    ,272.2,281,285.8
XS GIS Cut Line= 4
  1973981.241935232227.2199202061973524.67917393232230.109557934
1973227.04648791232363.0328934371972938.08271508232516.183693038
#Sta/Elev= 30
       0 2059.83    14.3 2055.58    27.6 2046.41   155.5 1976.01   179.4 1959.77
   204.7  1950.4   247.4 1945.94   316.3 1933.89   472.6 1900.61     497 1882.79
   502.3 1880.95     558  1877.3   604.2 1879.58   611.7 1877.31   627.1 1875.82
   637.1 1877.12   653.9 1879.27   684.1 1904.98   737.7 1941.09   780.8 1976.02
   791.9  1981.4   815.3 2002.47     907 2074.69   940.4 2098.37   981.3 2120.69
   988.7 2131.72   994.6 2136.29  1028.1 2149.22    1089 2176.97  1109.6 2189.19
#Mann= 3 ,-1 , 0
       0      .1       0   611.7    .045       0   637.1      .1       0
#XS Ineff= 2 , 0
          576.41 1883.44
Permanent Ineff=
       F       F
Bank Sta=611.7,637.1
XS Rating Curve= 0 ,0
Exp/Cntr(USF)=0,0
Exp/Cntr=0.3,0.1

Type RM Length L Ch R = 1 ,3677    ,381.2,378.8,374.7
XS GIS Cut Line= 4
1973729.84345264231975.8214378411973455.32786845232033.614192408
 1973021.8822092232091.4069469741972738.69771182232189.654629737
#Sta/Elev= 30
       0  2042.9      16 2037.96    99.8 2000.71   142.6 1978.38   164.7 1962.38
   200.7 1949.96   240.6 1930.09   324.9  1907.3   350.4 1904.36   366.9 1898.33
   380.2 1889.88     400 1869.86   406.6 1865.69   413.3 1864.63   462.9 1867.57
   476.8 1865.68  507.46 1866.26   522.5 1869.12   552.7  1887.9   568.8  1891.3
   625.1 1911.29   648.3 1914.52   661.5 1925.23   701.2 1951.75   720.6 1962.91
   860.8 2054.85   901.8 2083.39     912 2087.95   974.8 2133.24  1017.6  2167.4
#Mann= 3 ,-1 , 0
       0      .1       0   476.8    .045       0  507.46      .1       0
Bank Sta=476.8,507.46
XS Rating Curve= 0 ,0
Exp/Cntr(USF)=0,0
Exp/Cntr=0.3,0.1

Type RM Length L Ch R = 1 ,3298    ,366.4,367.3,368.4
XS GIS Cut Line= 4
1973556.46518894231626.1752727141973316.62525749231672.409476367
1972923.63452644231782.2157100441972599.99510086231854.456653252
#Sta/Elev= 30
       0 2035.89   126.7 1956.32   166.8 1935.17   186.9 1926.82   246.9 1894.52
   277.7 1880.16   325.4 1863.95   335.6 1861.36   366.3 1860.94  376.861853.788
   393.5  1850.3     404 1853.38   410.6  1854.9   448.1 1853.48   468.5 1855.14
   489.2  1868.5   547.8 1890.86   560.5 1898.04   574.1 1900.52   597.9 1911.48
   621.8 1930.82     676 1966.11     713 1995.98   766.7 2035.11   827.2 2073.55
   874.2  2109.1   920.9  2140.8   934.7 2148.53   941.5 2158.18   983.9 2178.11
#Mann= 5 ,-1 , 0
       0      .1       0  376.86    .045       0     404      .1       0
  584.26     .08       0   652.3      .1       0
Bank Sta=376.86,404
XS Rating Curve= 0 ,0
Exp/Cntr(USF)=0,0
Exp/Cntr=0.3,0.1

Type RM Length L Ch R = 1 ,2931    ,525.9,537,546.6
XS GIS Cut Line= 4
1973631.59576987231296.7565716851973417.76257798231302.535847142
1972839.83503231231415.2317185461972533.53343311231519.258676766
#Sta/Elev= 30
       0  2062.7   124.2 1981.73   183.2 1940.27   212.8 1915.34   239.5  1906.1
   266.2 1888.61   326.4 1861.85   393.3 1856.14   413.3 1846.72   426.7 1845.17
  436.211840.451   443.4 1838.68   470.1 1840.63   510.2 1841.08   559.6 1859.54
   577.1 1868.88   609.9 1873.94   623.9 1880.12   684.1 1926.82   694.1 1930.57
   717.5 1947.31   856.4 2059.91   963.8 2138.39   984.6 2150.66  1033.1 2191.25
    1047 2197.48  1057.4 2207.11  1074.7 2209.31  1088.6 2218.92  1126.2 2236.22
#Mann= 3 ,-1 , 0
       0      .1       0  436.21    .045       0   470.1      .1       0
Bank Sta=436.21,470.1
XS Rating Curve= 0 ,0
Exp/Cntr(USF)=0,0
Exp/Cntr=0.3,0.1

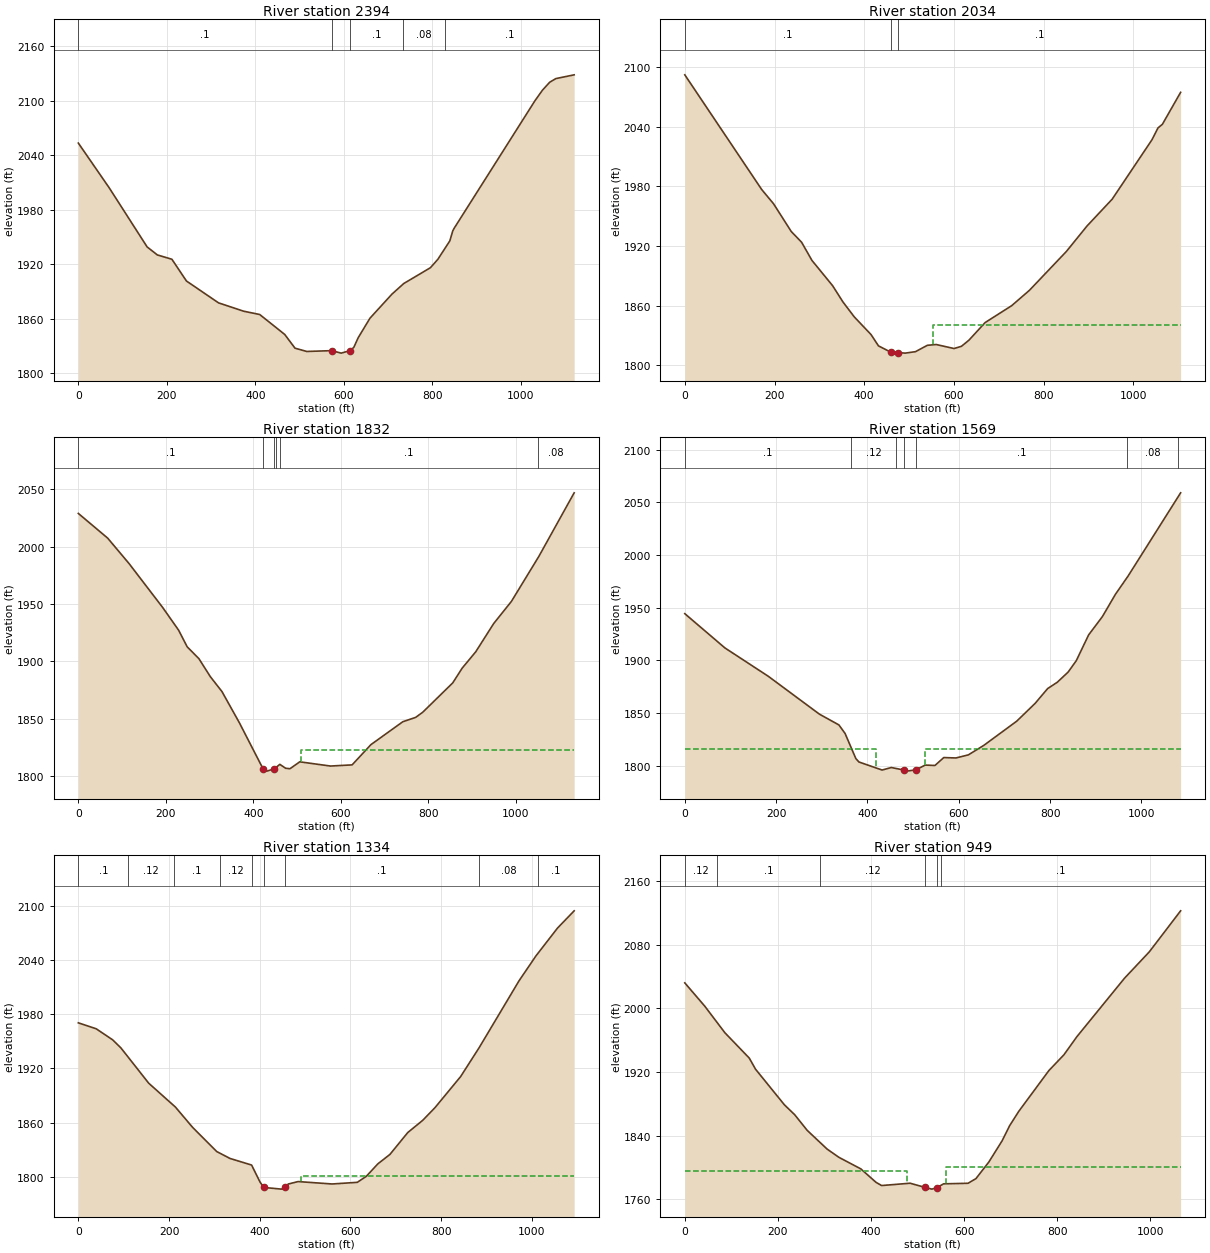
Type RM Length L Ch R = 1 ,2394    ,358.2,359.2,359.6
XS GIS Cut Line= 4
1973646.04395852230900.8762029041973342.63199704230926.882942459
1972874.51068505230851.752361523 1972542.2023463 230770.84250513
#Sta/Elev= 30
       0 2053.48    69.9 2004.11   155.5 1939.09   178.6 1930.26   211.5 1925.49
   244.4 1901.53   316.9 1877.45   373.5 1868.29     410 1864.61   466.5 1842.66
   489.8 1827.51   516.4 1823.91   572.9 1824.81   594.1 1822.08  614.391824.864
   622.7 1828.48   632.7 1839.16   659.2 1860.57   708.9 1887.08   735.7 1898.81
   795.8 1916.17   812.6  1925.4   839.7 1945.76   846.4 1956.86   849.8 1959.88
  1032.1 2100.14    1049 2111.72  1065.4 2120.51  1079.4 2124.53  1120.7 2128.67
#Mann= 5 ,-1 , 0
       0      .1       0   572.9    .045       0  614.39      .1       0
  734.52     .08       0  828.64      .1       0
Bank Sta=572.9,614.39
XS Rating Curve= 0 ,0
Exp/Cntr(USF)=0,0
Exp/Cntr=0.3,0.1

Type RM Length L Ch R = 1 ,2034    ,202.2,202.5,201.9
XS GIS Cut Line= 4
1973661.97113865230555.9032133321973280.64219016230588.588551774
 1972979.9370765230553.7241907691972561.56474444230590.767574337
#Sta/Elev= 30
       0 2092.23   171.5 1976.82   197.9  1962.5   237.4 1934.57   260.4 1923.82
   283.5 1905.51   329.6 1880.07   352.6 1863.74   377.8 1848.73   415.3 1830.89
   431.8 1819.55   460.6 1812.88   475.4 1812.78   491.3 1812.23   514.4 1813.71
   540.8  1820.1   560.6 1820.89   600.2 1816.86   616.8 1819.09   633.3 1825.16
   669.6 1842.97   728.9    1860   768.5 1875.47   850.8 1914.53   896.9 1940.19
   952.9 1967.12  1041.8 2027.04    1055  2038.8  1064.8 2042.45  1105.5 2074.61
#Mann= 3 ,-1 , 0
       0      .1       0   460.6    .045       0   475.4      .1       0
#XS Ineff= 2 , 0
                          553.68         1840.73
Permanent Ineff=
       F       F
Bank Sta=460.6,475.4
XS Rating Curve= 0 ,0
Exp/Cntr(USF)=0,0
Exp/Cntr=0.3,0.1

Type RM Length L Ch R = 1 ,1832    ,257.2,262.7,254.7
XS GIS Cut Line= 4
1973669.16106034230351.8450345231973331.07344613230395.189600448
1973004.54438283230357.6243099791972545.09198402230418.306702274
#Sta/Elev= 30
       0    2029    67.1 2007.44   116.1 1985.15   192.8 1946.89   229.2 1927.08
   248.8 1912.55   275.5 1902.28   301.6 1886.56   328.3  1873.5     368 1846.32
  422.141806.098   430.8  1804.1  447.751806.093   460.5 1810.02   473.7  1806.6
   483.6  1806.2     506 1812.22   576.1 1808.54   625.6 1809.55   668.6 1827.22
   741.5 1847.21   770.8 1850.99   786.9 1855.47   855.6 1881.12     877 1893.91
   908.2  1908.3   949.1 1932.89   989.6  1952.2  1052.4 1991.54    1133 2046.98
#Mann= 6 ,-1 , 0
       0      .1       0  422.14    .045       0  447.75      .1       0
  450.85     .12       0  460.85      .1       0 1049.54     .08       0
#XS Ineff= 2 , 0
                          508.88         1822.63
Permanent Ineff=
       F       F
Bank Sta=422.14,447.75
XS Rating Curve= 0 ,0
Exp/Cntr(USF)=0,0
Exp/Cntr=0.3,0.1

Type RM Length L Ch R = 1 ,1569    ,242.2,235.2,230.1
XS GIS Cut Line= 4
 1973575.6733661230197.2200725131973242.28291399230187.414470981
1972857.90333391230281.5482456941972518.62952088230391.370982859
#Sta/Elev= 30
       0 1944.34    87.9 1911.77   183.1 1884.78   294.7  1848.9   337.5 1838.62
     351 1830.54   374.6 1806.67   381.4  1803.4   432.1 1795.76   452.3 1798.15
   479.3 1795.79   486.1 1794.72   506.4 1795.98   526.6 1800.47   547.8 1800.08
   567.2  1807.6   593.9 1807.23   621.1 1810.17     655 1819.23   726.9 1842.17
   767.2 1859.08   794.7 1873.18   815.8 1879.17   839.6 1888.87   857.3  1899.6
   884.5  1924.2   914.6 1941.57   943.2 1962.79   970.7 1979.99  1085.9 2059.16
#Mann= 7 ,-1 , 0
       0      .1       0  363.53     .12       0  463.53      .1       0
   479.3    .045       0   506.4      .1       0  969.27     .08       0
 1079.27      .1       0
#XS Ineff= 2 , 0
          417.76 1815.52   526.4         1815.87
Permanent Ineff=
       F       F
Bank Sta=479.3,506.4
XS Rating Curve= 0 ,0
Exp/Cntr(USF)=0,0
Exp/Cntr=0.3,0.1

Type RM Length L Ch R = 1 ,1334    ,395,384.7,381.5
XS GIS Cut Line= 4
1973411.98330252229857.7169829791973143.24699379229947.295752557
1972712.69097227230161.1289444531972469.96140309230383.631049534
#Sta/Elev= 30
       0 1970.69    39.4 1964.09    75.8 1951.77    93.9 1942.84   155.2 1903.65
     214 1877.21   252.1 1854.54   305.2 1827.75   334.5 1820.08   382.1 1812.76
   400.4 1794.09   408.7  1787.9     448 1786.02  455.94 1787.91   462.7 1791.65
   484.7  1794.4   559.7 1791.74   615.2 1793.57   634.9  1800.2   660.5  1814.1
   687.1 1824.58   726.4 1848.85   759.4 1862.44   786.2 1876.37     843 1911.03
   883.8  1943.1   971.9 2017.49  1009.1 2045.06  1056.6 2075.92  1093.3 2095.08
#Mann= 9 ,-1 , 0
       0      .1       0     110     .12       0     210      .1       0
  313.27     .12       0  383.27      .1       0   408.7    .045       0
  455.94      .1       0     884     .08       0    1014      .1       0
#XS Ineff= 2 , 0
                          489.97         1800.99
Permanent Ineff=
       F       F
Bank Sta=408.7,455.94
XS Rating Curve= 0 ,0
Exp/Cntr(USF)=0,0
Exp/Cntr=0.3,0.1

Type RM Length L Ch R = 1 ,949     ,177.8,179.1,179
XS GIS Cut Line= 4
1973198.15011063229470.5055273831972964.08945463229583.201398788
1972565.31944812229869.2755338921972342.81734304230091.777638973
#Sta/Elev= 30
       0 2032.01    42.7 2002.91    86.1 1969.37   138.6 1937.44   151.9 1923.61
   213.9 1878.85   236.1 1866.34   262.9 1846.72   305.7 1823.17   331.1 1812.79
   378.2 1798.26   411.1 1781.26   422.8 1777.34     484 1780.25  516.911774.877
     531 1772.83  542.271774.875     556 1779.48   608.5 1780.18   625.5 1786.04
   653.2 1806.92   681.8 1833.65   697.9 1852.59   717.6 1870.68   782.2 1921.83
   814.5 1941.64   842.5 1964.52   944.6 2037.83   997.9 2070.99  1065.2 2122.55
#Mann= 6 ,-1 , 0
       0     .12       0      70      .1       0  289.78     .12       0
  516.91    .045       0  542.27     .12       0  549.78      .1       0
#XS Ineff= 2 , 0
          477.94 1795.92  560.46         1800.33
Permanent Ineff=
       F       F
Bank Sta=516.91,542.27
XS Rating Curve= 0 ,0
Exp/Cntr(USF)=0,0
Exp/Cntr=0.3,0.1

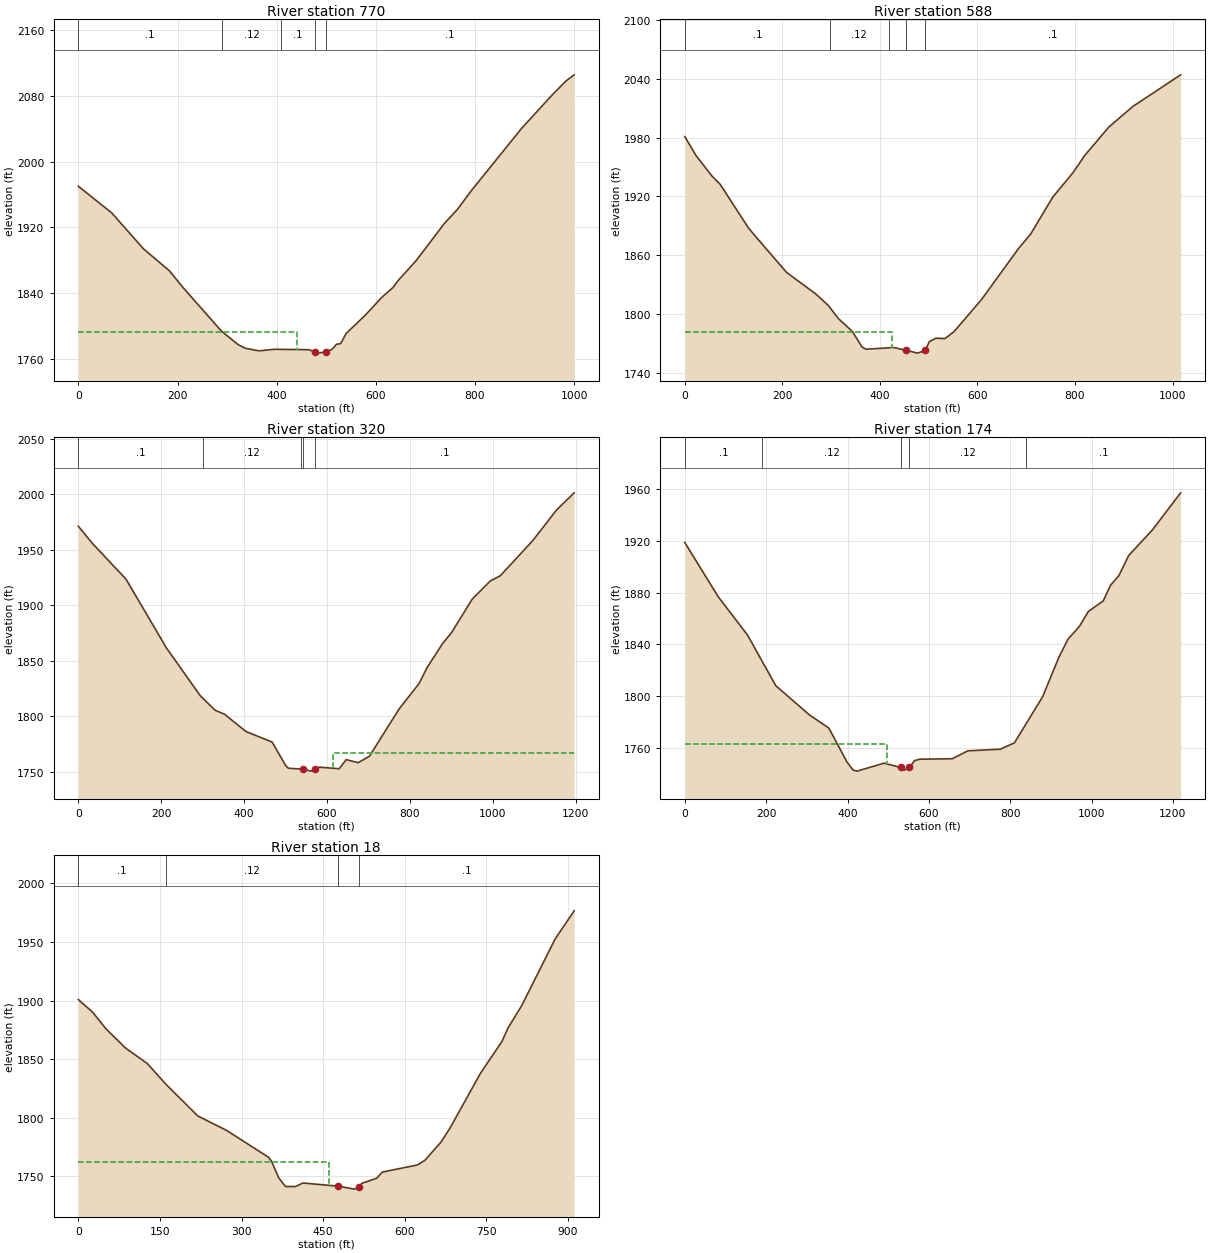
Type RM Length L Ch R = 1 ,770     ,182.4,182.5,178.5
XS GIS Cut Line= 4
1973080.89228134229341.9364045531972776.37540351 229510.63589556
1972570.50483821229643.5939689811972271.70658719229919.517712747
#Sta/Elev= 30
       0  1970.1    67.4 1937.69   131.5 1893.99   183.7 1867.42   209.9 1847.94
   288.7 1794.14   322.2 1777.79   336.7 1773.32   364.4 1770.22   395.6 1772.11
     465 1771.61   476.9 1768.85   481.5 1767.44  499.86 1768.81     512 1772.22
   520.6 1778.18   529.1 1779.04   540.1 1791.28   578.5 1813.42   612.9 1835.69
   635.2 1847.45   644.1 1855.03   681.4 1879.87   737.9 1924.66   764.7  1942.1
   791.5 1963.93   894.2 2040.57   956.7 2081.68   983.5 2097.94   999.9 2105.38
#Mann= 5 ,-1 , 0
       0      .1       0     290     .12       0  408.12      .1       0
   476.9    .045       0  499.86      .1       0
#XS Ineff= 2 , 0
          440.99 1792.57
Permanent Ineff=
       F       F
Bank Sta=476.9,499.86
XS Rating Curve= 0 ,0
Exp/Cntr(USF)=0,0
Exp/Cntr=0.3,0.1

Type RM Length L Ch R = 1 ,588     ,276.6,267.3,255.6
XS GIS Cut Line= 4
1972978.53764327229167.0935659091972767.59408911229297.127263684
1972449.73393899 229528.298281951972224.34219618229828.820605696
#Sta/Elev= 30
       0 1980.94    22.8 1961.75      55 1941.07    72.4 1932.29   130.1 1888.01
   142.1 1880.72   208.8 1842.25   268.1 1820.48   294.4  1808.5   315.1 1795.03
   343.6 1782.01   363.3 1766.16   371.4 1763.91   428.3 1765.66  454.141762.785
   477.2 1759.91  493.341762.783   501.3 1771.69   514.7 1775.13   533.5 1774.77
   552.3 1782.01   608.7 1814.85   683.7 1866.37   709.4 1881.68     754 1918.87
   796.2 1944.32   820.1 1961.79   869.3 1990.63   918.5 2011.66  1016.5 2043.97
#Mann= 5 ,-1 , 0
       0      .1       0   297.8     .12       0   417.8      .1       0
  454.14    .045       0  493.34      .1       0
#XS Ineff= 2 , 0
          424.64 1781.13
Permanent Ineff=
       F       F
Bank Sta=454.14,493.34
XS Rating Curve= 0 ,0
Exp/Cntr(USF)=0,0
Exp/Cntr=0.3,0.1

Type RM Length L Ch R = 1 ,320     ,146.1,146.6,148
XS GIS Cut Line= 4
1972744.47698728228779.8821103141972527.75415765229039.949505863
1972267.68676211229499.4019046671972137.65306433229802.813866141
#Sta/Elev= 30
       0 1971.25    33.4 1956.02     115 1923.56   212.8 1861.41   294.3 1818.39
   330.2 1805.28   352.8 1801.73   404.7  1786.1   467.6 1776.64   500.9 1755.21
   506.9 1753.02  543.241752.186   560.8 1750.41   570.81752.188   581.5 1753.97
   629.7 1752.59   646.5  1760.8   675.4 1758.04   702.6 1763.88   774.1 1806.45
   822.3 1829.41     842    1844     879 1865.41   900.5  1875.2   950.7 1905.56
     994 1921.82  1018.2 1926.54  1096.8 1958.31  1153.9 1985.84  1196.6 2001.37
#Mann= 5 ,-1 , 0
       0      .1       0     300     .12       0  538.53      .1       0
  543.24    .045       0   570.8      .1       0
#XS Ineff= 2 , 0
                          613.75         1766.56
Permanent Ineff=
       F       F
Bank Sta=543.24,570.8
XS Rating Curve= 0 ,0
Exp/Cntr(USF)=0,0
Exp/Cntr=0.3,0.1

Type RM Length L Ch R = 1 ,174     ,136.6,155.7,171.1
XS GIS Cut Line= 4
1972672.32630968228737.2866105681972407.84947143228967.637405165
1972271.34529686229199.6945019441972076.82684809229766.186826434
#Sta/Elev= 30
       0 1918.48      82 1876.82   154.1 1847.29   223.8 1808.21   306.5 1785.75
   354.2 1775.62   398.7  1749.5   414.1 1743.17   423.7 1742.49     490 1748.63
   530.8 1745.31   539.5 1743.21  552.09 1745.31   565.1 1750.58   577.6 1751.67
   657.7 1752.03   695.8 1758.12   775.6 1759.35   810.3 1764.24   879.7 1799.77
   919.7  1830.2   942.1 1844.11   969.9 1853.83     992 1865.37  1028.8  1873.6
  1046.5 1885.58    1067 1892.91  1091.3  1908.5  1150.2 1928.43  1218.9 1956.74
#Mann= 5 ,-1 , 0
       0      .1       0     190     .12       0   530.8    .045       0
  552.09     .12       0  839.96      .1       0
#XS Ineff= 2 , 0
          497.42 1763.58
Permanent Ineff=
       F       F
Bank Sta=530.8,552.09
XS Rating Curve= 0 ,0
Exp/Cntr(USF)=0,0
Exp/Cntr=0.3,0.1

Type RM Length L Ch R = 1 ,18      ,,,
XS GIS Cut Line= 4
1972650.14438131228725.3424952931972390.78644961228959.105894254
1972109.24658955229035.8894924531971839.65084476229054.658816457
#Sta/Elev= 30
       0 1900.82    25.9 1890.24    51.4 1875.59    86.9 1859.46   126.7 1846.28
   160.6 1828.81   219.4 1801.64   272.4 1789.28   349.2 1766.48   354.7 1763.34
   368.3 1748.79   380.8 1741.42   398.9 1741.41   412.8  1744.4     477 1741.76
   507.7  1739.2  515.311740.884   521.3  1744.2   548.5  1748.5   558.7 1753.72
   623.4 1759.83   637.3 1763.93   666.7 1779.44   683.5 1791.58     739 1837.93
   778.5 1865.08   789.5 1876.43   814.7 1895.58   876.5 1952.67   911.2 1976.48
#Mann= 4 ,-1 , 0
       0      .1       0   160.6     .12       0     477    .045       0
  515.31      .1       0
#XS Ineff= 2 , 0
           460.1 1762.14
Permanent Ineff=
       F       F
Bank Sta=477,515.31
XS Rating Curve= 0 ,0
Exp/Cntr(USF)=0,0
Exp/Cntr=0.3,0.1
LCMann Table=0

Chan Stop Cuts=-1
Use User Specified Reach Order=0
Composite Channel Slope=5